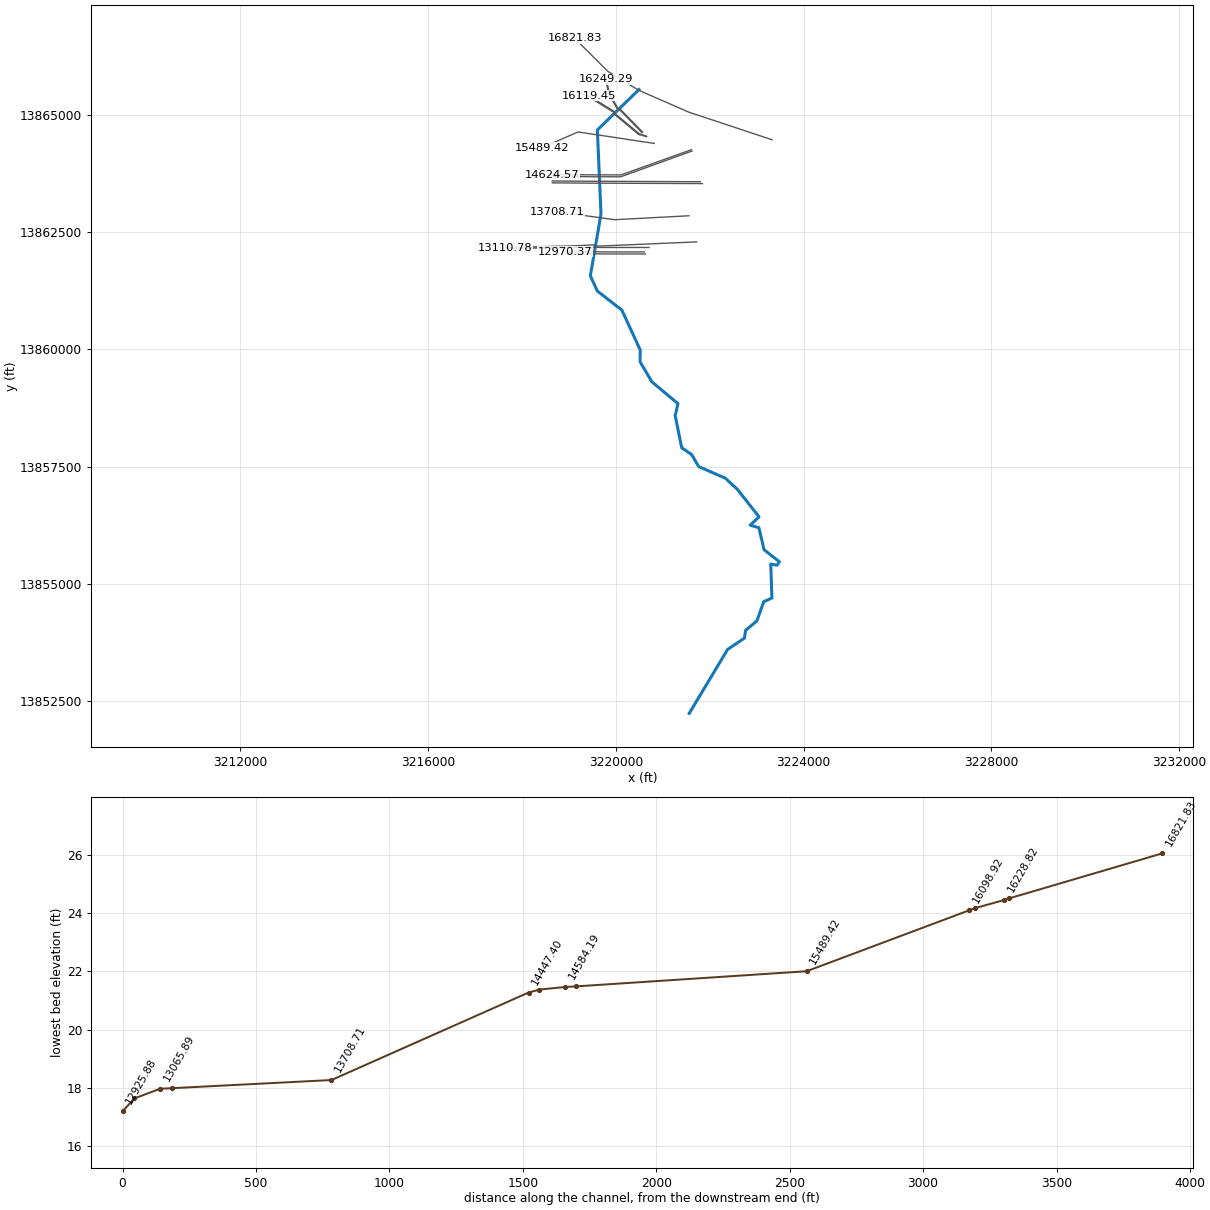
--- O200-00-00.prj (project) ---

Proj Title=O200-00-00
Current Plan=p05
Default Exp/Contr=.3,.1
English Units
Geom File=g04
Flow File=f01
Flow File=f03
Plan File=p01
Plan File=p05
Y Axis Title=Elevation
X Axis Title(PF)=Main Channel Distance
X Axis Title(XS)=Station
BEGIN DESCRIPTION:
Goose Creek Watershed
Spring Gully
HCFCD Unit O200-00-00
Flood Hazard, Floodway Model
10, 2, 1, 0.2% Event
Filename O2000000.prj
Prepared By:  FTN	DATE:  May 2003
Reviewed By:	DATE:
STATUS (FINAL)
Starting water surface elevation based upon mean high tide (MHT) at Morgans Point with an elevation of 1.5' used for all profiles.
Manning's n data and flows and flow change locations adapted from HEC-2 data.
END DESCRIPTION:
DSS Export Rating Curves= 0
DSS Export Rating Curve Sorted= 0
DSS Export Volume Flow Curves= 0
DXF OffsetX= 0
DXF OffsetY= 0
DXF ScaleX= 1
DXF ScaleY= 10

--- O200-00-00.p05 (plan) ---

Plan Title=Floodway
Version=Version 3.0.1  Mar 2001
Short Identifier=Floodway0607
Geom File=g04
Flow File=f03
Subcritical Flow
K Sum by GR= 0
Std Step Tol= 0.01
Critical Tol= 0.01
Num of Std Step Trials= 20
Max Error Tol= 0.3
Flow Tol Ratio= 0.001
Split Flow NTrial= 30
Split Flow Tol= 0.02
Split Flow Ratio= 0.02
Log Output Level= 0
Friction Slope Method= 1
Unsteady Friction Slope Method= 2
Parabolic Critical Depth
Global Vel Dist= 0 , 0 , 0
Global Log Level= 0
CheckData=True
Encroach Param=-1 ,0,0, 2
Encroach River=O200-00-00
Encroach Reach=Spring Gully
Encroach Node=16821.83
       1    3024    3102
Encroach Node=16249.29
       1     682     759
Encroach Node=16228.82
       1     781     863
Encroach Node=16174
       1     781     863
Encroach Node=16119.45
       1     768     878
Encroach Node=16098.92
       1     817     935
Encroach Node=15489.42
       1  601.91     730
Encroach Node=14624.57
       1     962    1030
Encroach Node=14584.19
       1     962    1030
Encroach Node=14536
       1     956    1030
Encroach Node=14487.19
       1     964    1030
Encroach Node=14447.40
       1     430     498
Encroach Node=13708.71
       1     702     776
Encroach Node=13110.78
       1  276.63  339.66
Encroach Node=13065.89
       1     275     335
Encroach Node=13018
       1     259     335
Encroach Node=12970.37
       1     293     347
Encroach Node=12925.88
       1  299.83  348.82
Encroach Node=11635.64
       1  115.62  179.03
Encroach Node=11389.66
       1  123.78  178.76
Encroach Node=10608.88
       1     220     288
Encroach Node=9378.034
       1  695.28  756.75
Encroach Node=8388.259
       1  689.65     761
Encroach Node=7354.025
       1     560  628.86
Encroach Node=7303.709
       1     555     625
Encroach Node=7175
       1     555     625
Encroach Node=7047.162
       1     546     623
Encroach Node=6987.469
       1  570.41  638.75
Encroach Node=6788.494
       1     468     532
Encroach Node=6605.805
       1     483     541
Encroach Node=6510.014
       1     506     555
Encroach Node=6320
       1     506     555
Encroach Node=6129.636
       1     506     555
Encroach Node=6090.962
       1     354     393
Encroach Node=5105.044
       1  151.99  218.36
Encroach Node=4311.189
       1  552.55  703.27
Encroach Node=3897.820
       1     538     722
Encroach Node=3868.363
       1     595     698
Encroach Node=3816
       1     595     710
Encroach Node=3763.187
       1     626     710
Encroach Node=3732.799
       1     575     655
Encroach Node=3709.018
       1   620.6  723.07
Encroach Node=3647.172
       1  629.11  731.58
Encroach Node=3605
       1  629.11  731.58
Encroach Node=3563.238
       1  635.83   679.7
Encroach Node=3532.235
       1  633.83   677.7
Encroach Node=2428.452
       1     867    1022
Encroach Node=1685.034
       1    1184 1266.27
Encroach Node=249.149
       1 1729.41 2063.65
Encroach Reach=O200-00-00_0002
Encroach Node=16821.83
       1    3024    3102
Encroach Node=16249.29
       1     682     759
Encroach Node=16228.82
       1     781     863
Encroach Node=16174
       1     781     863
Encroach Node=16119.45
       1     768     878
Encroach Node=16098.92
       1     817     935
Encroach Node=15489.42
       1  601.91     730
Encroach Node=14624.57
       1     962    1030
Encroach Node=14584.19
       1     962    1030
Encroach Node=14536
       1     956    1030
Encroach Node=14487.19
       1     964    1030
Encroach Node=14447.40
       1     430     498
Encroach Node=13708.71
       1     702     776
Encroach Node=13110.78
       1  276.63  339.66
Encroach Node=13065.89
       1     275     335
Encroach Node=13018
       1     259     335
Encroach Node=12970.37
       1     293     347
Encroach Node=12925.88
       1  299.83  348.82
Encroach Node=11635.64
       1  115.62  179.03
Encroach Node=11389.66
       1  123.78  178.76
Encroach Node=10608.88
       1     220     288
Encroach Node=9378.034
       1  695.28  756.75
Encroach Node=8388.259
       1  689.65     761
Encroach Node=7354.025
       1     560  628.86
Encroach Node=7303.709
       1     555     625
Encroach Node=7175
       1     555     625
Encroach Node=7047.162
       1     546     623
Encroach Node=6987.469
       1  570.41  638.75
Encroach Node=6788.494
       1     468     532
Encroach Node=6605.805
       1     483     541
Encroach Node=6510.014
       1     506     555
Encroach Node=6320
       1     506     555
Encroach Node=6129.636
       1     506     555
Encroach Node=6090.962
       1     354     393
Encroach Node=5105.044
       1  151.99  218.36
Encroach Node=4311.189
       1  552.55  703.27
Encroach Node=3897.820
       1     538     722
Encroach Node=3868.363
       1     595     698
Encroach Node=3816
       1     595     710
Encroach Node=3763.187
       1     626     710
Encroach Node=3732.799
       1     575     655
Encroach Node=3709.018
       1   620.6  723.07
Encroach Node=3647.172
       1  629.11  731.58
Encroach Node=3605
       1  629.11  731.58
Encroach Node=3563.238
       1  635.83   679.7
Encroach Node=3532.235
       1  633.83   677.7
Encroach Node=2428.452
       1     867    1022
Encroach Node=1685.034
       1    1184 1266.27
Encroach Node=249.149
       1 1729.41 2063.65
Computation Interval=1HOUR
Output Interval=1HOUR
Run HTab= 0
Run UNet= 0
Run PostProcess= 0
UNET Theta= 1
UNET ZTol= 0.02
UNET ZSATol= 0.1
UNET MxIter= 20
UNET MaxInSteps= 20
UNET DtIC= 0
UNET DtMin= 0
UNET MaxCRTS= 20
UNET WFStab= 2
UNET SFStab= 1
UNET WFX= 1
UNET SFX= 1
UNET Convert EG Bridges=-1
UNET Use Existing IB Tables=-1
Instantaneous Interval=1HOUR
Write IC File= 0
Write Velocity= 0
Write Detailed= 0

--- O200-00-00.p01 (plan) ---

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Plan Title=FEMA Effective June 2007
Short Identifier=FEMAeff0607
Geom File=g04
Flow File=f01
Encroach Param=-1 ,0,0, 0

--- O200-00-00.f03 (steady flow) ---

Flow Title=Floodway
Version=Version 3.0.1  Mar 2001
Number of Profiles= 2
Profile Names=1PCT_100yr, 1PCTFloodway_100yrFW
River Rch & RM=O200-00-00,O200-00-00_0002,16821.83
     855     855
River Rch & RM=O200-00-00,O200-00-00_0002,16249.29
     869     869
River Rch & RM=O200-00-00,O200-00-00_0002,16098.92
     927     927
River Rch & RM=O200-00-00,O200-00-00_0002,15489.42
    1097    1097
River Rch & RM=O200-00-00,O200-00-00_0002,14624.57
    1135    1135
River Rch & RM=O200-00-00,O200-00-00_0002,14447.40
    1310    1310
River Rch & RM=O200-00-00,O200-00-00_0002,13708.71
    1471    1471
River Rch & RM=O200-00-00,O200-00-00_0002,13110.78
    1500    1500
River Rch & RM=O200-00-00,O200-00-00_0002,12925.88
    1717    1717
River Rch & RM=O200-00-00,O200-00-00_0002,11635.64
    1762    1762
River Rch & RM=O200-00-00,O200-00-00_0002,11389.66
    1912    1912
River Rch & RM=O200-00-00,O200-00-00_0002,9378.034
    1067    1067
River Rch & RM=O200-00-00,O200-00-00_0002,8388.259
    1190    1190
River Rch & RM=O200-00-00,O200-00-00_0002,7354.025
    1229    1229
River Rch & RM=O200-00-00,O200-00-00_0002,7047.162
    1281    1281
River Rch & RM=O200-00-00,O200-00-00_0002,6605.805
    1293    1293
River Rch & RM=O200-00-00,O200-00-00_0002,6510.014
    1344    1344
River Rch & RM=O200-00-00,O200-00-00_0002,6090.962
    1474    1474
River Rch & RM=O200-00-00,O200-00-00_0002,5105.044
    1588    1588
River Rch & RM=O200-00-00,O200-00-00_0002,4311.189
    1656    1656
River Rch & RM=O200-00-00,O200-00-00_0002,3868.363
    1709    1709
River Rch & RM=O200-00-00,O200-00-00_0002,3532.235
    1895    1895
River Rch & RM=O200-00-00,O200-00-00_0002,2428.452
    2031    2031
River Rch & RM=O200-00-00,O200-00-00_0002,1685.034
    2324    2324
Boundary for River Rch & Prof#=O200-00-00,O200-00-00_0002, 1
Up Type= 0
Dn Type= 1
Dn Known WS=1.5
Boundary for River Rch & Prof#=O200-00-00,O200-00-00_0002, 2
Up Type= 0
Dn Type= 1
Dn Known WS=1.5
DSS Import GetInterval= 0
DSS Import GetPeak= 0
DSS Import FillOption= 0

--- O200-00-00.f01 (steady flow) ---

Flow Title=FEMA Effective June 2007
Version=Version 3.0.1  Mar 2001
Number of Profiles= 4
Profile Names=10PCT_10yr, 2PCT_50yr, 1PCT_100yr, 0.2PCT_500yr
River Rch & RM=O200-00-00,O200-00-00_0002,16821.83
     399     697     855    1313
River Rch & RM=O200-00-00,O200-00-00_0002,16249.29
     407     709     869    1333
River Rch & RM=O200-00-00,O200-00-00_0002,16098.92
     443     759     927    1415
River Rch & RM=O200-00-00,O200-00-00_0002,15489.42
     539     904    1097    1620
River Rch & RM=O200-00-00,O200-00-00_0002,14624.57
     561     937    1135    1666
River Rch & RM=O200-00-00,O200-00-00_0002,14447.40
     664    1087    1310    1870
River Rch & RM=O200-00-00,O200-00-00_0002,13708.71
     760    1226    1471    2054
River Rch & RM=O200-00-00,O200-00-00_0002,13110.78
     781    1252    1500    2097
River Rch & RM=O200-00-00,O200-00-00_0002,12925.88
     948    1451    1717    2429
River Rch & RM=O200-00-00,O200-00-00_0002,11635.64
     984    1492    1762    2497
River Rch & RM=O200-00-00,O200-00-00_0002,11389.66
    1106    1631    1912    2729
River Rch & RM=O200-00-00,O200-00-00_0002,9378.034
     743     964    1067    1280
River Rch & RM=O200-00-00,O200-00-00_0002,8388.259
     834    1068    1190    1407
River Rch & RM=O200-00-00,O200-00-00_0002,7354.025
     863    1102    1229    1446
River Rch & RM=O200-00-00,O200-00-00_0002,7047.162
     896    1147    1281    1519
River Rch & RM=O200-00-00,O200-00-00_0002,6605.805
     903    1157    1293    1535
River Rch & RM=O200-00-00,O200-00-00_0002,6510.014
     935    1202    1344    1608
River Rch & RM=O200-00-00,O200-00-00_0002,6090.962
    1014    1314    1474    1792
River Rch & RM=O200-00-00,O200-00-00_0002,5105.044
    1083    1412    1588    1957
River Rch & RM=O200-00-00,O200-00-00_0002,4311.189
    1124    1470    1656    2055
River Rch & RM=O200-00-00,O200-00-00_0002,3868.363
    1156    1516    1709    2132
River Rch & RM=O200-00-00,O200-00-00_0002,3532.235
    1266    1675    1895    2409
River Rch & RM=O200-00-00,O200-00-00_0002,2428.452
    1347    1792    2031    2615
River Rch & RM=O200-00-00,O200-00-00_0002,1685.034
    1517    2042    2324    3064
Boundary for River Rch & Prof#=O200-00-00,O200-00-00_0002, 1
Up Type= 0
Dn Type= 1
Dn Known WS=1.5
Boundary for River Rch & Prof#=O200-00-00,O200-00-00_0002, 2
Up Type= 0
Dn Type= 1
Dn Known WS=1.5
Boundary for River Rch & Prof#=O200-00-00,O200-00-00_0002, 3
Up Type= 0
Dn Type= 1
Dn Known WS=1.5
Boundary for River Rch & Prof#=O200-00-00,O200-00-00_0002, 4
Up Type= 0
Dn Type= 1
Dn Known WS=1.5
DSS Import GetInterval= 0
DSS Import GetPeak= 0
DSS Import FillOption= 0

--- O200-00-00.g04 (geometry) ---

Geom Title=O200-00-00 June 2007
Version=Version 3.0.1  Mar 2001

River Reach=O200-00-00      ,O200-00-00_0002
Reach XY= 30
     3220492.113    13865538.306     3219606.549     13864677.72
     3219683.148     13862886.19     3219456.684    13861569.164
     3219606.371    13861245.237     3220128.831      13860839.2
     3220520.685    13859987.343     3220515.305    13859740.752
     3220766.865    13859312.111     3221323.181    13858846.622
     3221264.143    13858590.036     3221403.927    13857905.224
     3221611.063     13857765.34     3221766.126    13857504.646
     3222331.242    13857258.733     3222589.914    13857020.506
     3223051.195    13856433.687     3222861.955      13856256.6
     3223047.723    13856202.779     3223158.751    13855732.431
     3223483.496    13855478.805     3223437.656    13855403.481
      3223300.87    13855427.123     3223325.461    13854702.725
     3223150.584    13854626.768     3223005.464    13854217.289
     3222763.998    13854015.374       3222741.1    13853850.927
     3222380.982    13853608.419     3221562.928    13852246.774

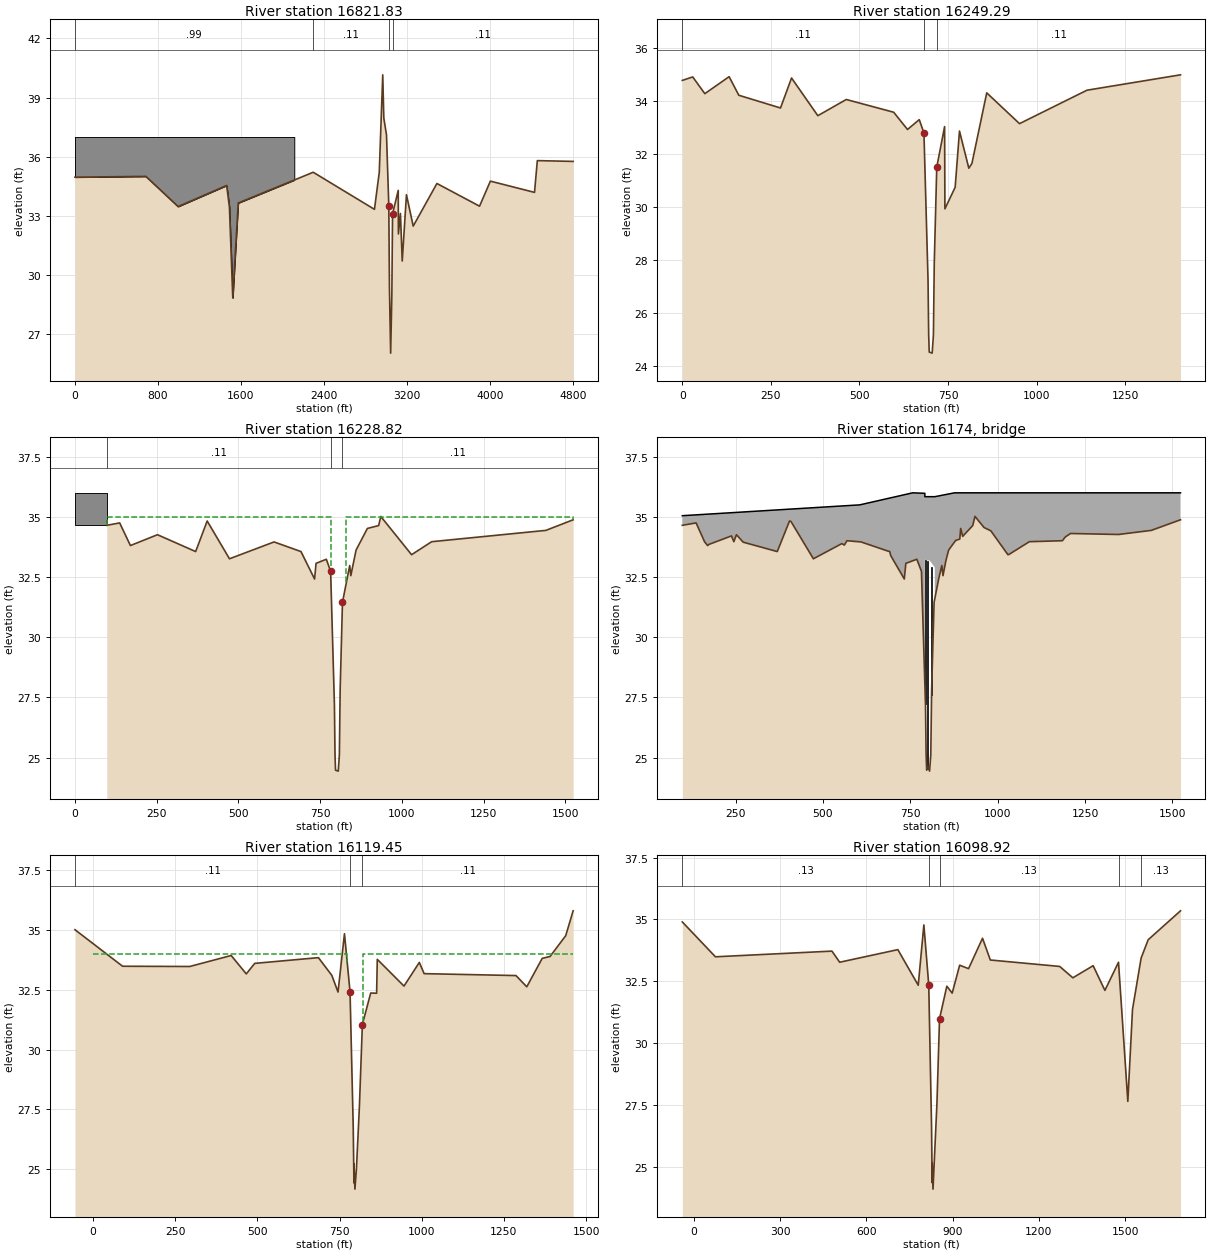
Type RM Length L Ch R = 1 ,16821.83,857.06,572.55,612.76
BEGIN DESCRIPTION:
461v12
Bank Station offset =      1958
LOB blocked at watershed divide
LOB and ROB > channel reach length due to the fact that the floodplain contracting at structure. (Stream is more direct, OB are curved.)
END DESCRIPTION:
XS GIS Cut Line= 6
     3223327.496    13864468.801      3221549.93     13865059.08
     3220495.187    13865519.826     3220453.708    13865544.302
     3219829.071    13865926.266     3219123.753    13866630.011
#Sta/Elev= 30
       0   34.96  683.33      35  993.99   33.47 1461.96   34.54 1488.66   33.44
 1521.02   28.84 1573.47   33.65 2296.12   35.21 2886.17   33.33 2932.55   35.21
 2965.95   40.15 2976.28   37.96 3002.12   37.11 3024.43   33.52 3030.63   29.32
 3042.18   26.04 3053.83   29.02 3060.51    33.1 3115.29   34.29 3116.95   32.08
  3136.3   33.12 3153.89   30.71  3194.4   34.07 3259.56   32.48 3487.93   34.64
 3898.96   33.49 4003.24   34.76 4428.59   34.19 4455.59    35.8 4800.68   35.76
#Mann= 4 ,-1 , 0
       0     .99       0 2296.12     .11       0 3024.43    .045       0
 3060.51     .11       0
#Block Obstruct= 2 , 0
       0 2113.44      37    4799       0      36
Bank Sta=3024.43,3060.51
XS Rating Curve= 0
Exp/Cntr=.3,.1

Type RM Length L Ch R = 1 ,16249.29,27.79,20.47,18.75
BEGIN DESCRIPTION:
461s7u - xs 4/4 of UP railroad spur
Bank Station offset =      4295
xsec 4/4 of UP Railroad Spur
No high points found on LIDAR to extend the LOB and ROB to contain the 500yr profile (extension on 500yr profile < 1')
END DESCRIPTION:
XS GIS Cut Line= 6
     3220569.552    13864633.862     3220092.552    13865120.653
     3220048.401    13865137.676     3220040.359    13865147.058
     3219868.572    13865429.348     3219796.562    13865756.057
#Sta/Elev= 30
       0   34.78   29.39   34.91   63.52   34.28  132.12   34.92  159.46   34.22
  277.14   33.74  308.33   34.87   382.5   33.45  462.86   34.06  596.62   33.58
  635.65   32.93  668.81    33.3  682.02    32.8  693.58   27.26  695.37    25.2
  696.97   24.54  705.27    24.5  708.77   25.18  711.17   27.89  718.21   31.51
  740.36   33.04  741.21   29.94  770.12   30.75  782.35   32.87  808.74   31.47
  817.47   31.65  859.28   34.31  951.79   33.15 1142.25   34.41 1406.22   34.99
#Mann= 3 , 0 , 0
       0     .11       0  682.02    .045       0  718.21     .11       0
#Block Obstruct= 2 , 0
       0       0      36    1406       0      36
Bank Sta=682.02,718.21
XS Rating Curve= 0
Exp/Cntr=.5,.3

Type RM Length L Ch R = 1 ,16228.82,137.1,109.37,93.98
BEGIN DESCRIPTION:
Copy of 461s7u - xs 3/4 of UP railroad spur
Bank Station offset =      4292
xsec 3/4 of UP Railroad Spur
No high points found on LIDAR to extend the LOB and ROB to contain the 500yr profile (extension on 500yr profile < 1')
END DESCRIPTION:
XS GIS Cut Line= 6
     3220556.592    13864621.182     3220086.373    13865103.621
     3220039.634    13865121.736     3220024.463    13865138.268
     3219849.947    13865443.376     3219777.496    13865763.683
#Sta/Elev= 30
   97.37   34.65  136.84   34.75  169.62   33.81  252.39   34.26  369.18   33.56
  404.35   34.83   472.6   33.26  608.94   33.96  691.21   33.56  732.85   32.42
  737.31   33.07  768.72   33.24  781.93   32.74  793.49    27.2  795.28   25.14
  796.88   24.48  805.18   24.44  808.68   25.12  811.08   27.83  818.12   31.45
  840.27   32.98  843.65   32.56   859.7   33.62  894.26   34.52  928.82   34.64
  935.25   35.02 1029.44   33.43 1090.96   33.97 1440.21   34.44 1523.54   34.88
#Mann= 3 , 0 , 0
   97.37     .11       0  781.93    .045       0  818.12     .11       0
#XS Ineff= 2 , 0
   97.37  781.68      35  830.19   97.37      35
Permanent Ineff=
       F       F
#Block Obstruct= 2 , 0
       0   97.37      36 1523.54       0      36
Bank Sta=781.93,818.12
XS Rating Curve= 0
Exp/Cntr=.5,.3

Type RM Length L Ch R = 3 ,16174   ,,,
BEGIN DESCRIPTION:
461s6/461s7, Union Pacific RR
Downstream i/e flow elevations decreased to avoid negative changes in WSEL at xsec 2/4
The UP rail road in the two directions is modeled as one structure. Road width represents the combined structure
END DESCRIPTION:
Bridge Culvert--1,0,-1,-1, 0
Deck Dist Width WeirC Skew NumUp NumDn MinLoCord MaxHiCord MaxSubmerge Is_Ogee
27.435,54.5,2.6,0, 10, 10, , , .95, 0, 0,0,,
   97.37  605.37  756.92  791.67  791.68  806.15  820.19   820.2  876.67 1523.54
   35.05    35.5      36   35.98   35.84   35.84   35.84   35.84      36      36
                                   33.22   33.18    32.9
     -55     597  748.55   783.3  783.31  797.78  811.82  811.83   868.3    1461
   35.05    35.5      36   35.98   35.84   35.84   35.84   35.84      36      36
                                   33.22   33.18    32.9
Pier Skew, UpSta & Num, DnSta & Num=  ,793.39, 4 ,785.02, 4 , 3 , 3 , 0 ,,
       1       1     1.5     1.5
   24.65   31.72   31.72   33.22
       1       1     1.5     1.5
   24.65   31.72   31.72   33.22
Pier Skew, UpSta & Num, DnSta & Num=  ,798.56, 4 ,790.19, 4 , 3 , 3 , 0 ,,
       1       1     1.5     1.5
    25.9   31.68   31.68   33.18
       1       1     1.5     1.5
    25.9   31.68   31.68   33.18
Pier Skew, UpSta & Num, DnSta & Num=  ,810.89, 4 ,802.52, 4 , 3 , 3 , 0 ,,
       1       1     1.5     1.5
    28.6    31.4    31.4    32.9
       1       1     1.5     1.5
    28.6    31.4    31.4    32.9
BR Coef=-1 , 0 , 0 ,, 0 ,,,.6,0,,0,
WSPro=,,,, 1 ,,,, 0 ,,,, 0 ,,,,-1 ,-1 ,-1 , 0 , 0 , 0 , 0 , 0
BR U #Sta/Elev= 56
   97.37   34.65  136.84   34.75  160.94   33.97  169.62   33.81  174.17   33.86
  238.13   34.21   244.9   33.97  252.39   34.26  271.48   33.95  369.18   33.56
  404.35   34.83   408.4   34.81   472.6   33.26  554.07   33.89  561.36   33.83
  568.85   34.01  608.94   33.96  685.91   33.58  691.21   33.56  694.07   33.39
  732.85   32.42  737.31   33.07  768.72   33.24  781.93   32.74  793.49    27.2
  795.28   25.14  796.88   24.48  801.08   24.64  805.18   24.44  808.68   25.12
  811.08   27.83  818.12   31.45  831.09   32.41  840.27   32.98  843.65   32.56
  851.65   33.16   859.7   33.62  879.85   34.02  891.72   34.08  894.26   34.52
  900.01   34.19  928.82   34.64  931.16   34.78  935.25   35.02  961.01   34.56
  980.66   34.42 1029.44   33.43  1032.5   33.44 1090.96   33.97 1185.55   34.01
 1192.28   34.14 1195.14   34.18 1208.66   34.31 1346.25   34.27 1440.21   34.44
 1523.54   34.88
BR U #Mann= 3
   97.37     .11  781.93     .04  818.12     .11
BR U Banks=781.93,818.12
BR D #Sta/Elev= 54
     -55   35.02     -20   34.65       0   34.28   89.93   33.49  108.56   33.48
  257.28   33.49  267.66    33.5   294.4   33.48  420.29   33.94  466.28   33.17
  491.94   33.61   527.7   33.65  570.25   33.72  685.71   33.85  726.43   33.11
  745.37   32.41  764.96   34.85  781.93   32.42  791.61   26.75  793.77   24.42
  793.91   25.22  796.76   24.16  798.35    24.5  801.47   25.03   810.4   27.62
  819.42   31.05  844.82   32.37   862.8   32.36  864.79   33.78  877.92   33.62
  921.64   33.22   928.7    33.1  930.89   32.71  946.07   32.66  970.92   33.09
   992.7   33.65 1007.33   33.18 1093.74   33.31 1119.66    33.2 1128.02   33.22
 1143.74   33.12 1183.87   33.19  1241.6   33.16 1262.76   32.94 1286.79    33.1
 1319.61   32.63 1328.63   32.87 1337.04   33.08  1341.6    33.2  1366.6   33.82
 1390.49    33.9  1438.1   34.77 1447.44   35.03 1460.65   35.81
BR D #Mann= 3
     -55     .11  781.93     .04  819.42     .11
BC Design=,, 0 ,, 0 ,,,,,,

Type RM Length L Ch R = 1 ,16119.45,19.5,20.53,21.68
BEGIN DESCRIPTION:
Copy of 461s6d - xs 2/4 of UP railroad spur
Bank Station offset =      4203
xsec 2/4 of UP Railroad Spur
LOB extended using LIDAR data to contain 500 yr profile initially. No more high points found.
ROB trimmed to contain 500yr profile
END DESCRIPTION:
XS GIS Cut Line= 6
 3220651.429012813864547.0928355     3220496.214    13864598.678
     3219980.086    13865027.998     3219962.927    13865069.128
     3219956.363    13865075.907 3219423.985983313865406.6242331
#Sta/Elev= 30
     -55   35.02   89.93   33.49   294.4   33.48  420.29   33.94  466.28   33.17
  491.94   33.61  685.71   33.85  726.43   33.11  745.37   32.41  764.96   34.85
  781.93   32.42  791.61   26.75  793.77   24.42  793.91   25.22  796.76   24.16
  801.47   25.03   810.4   27.62  819.42   31.05  844.82   32.37   862.8   32.36
  864.79   33.78  946.07   32.66   992.7   33.65 1007.33   33.18 1286.79    33.1
 1319.61   32.63  1366.6   33.82 1390.49    33.9  1438.1   34.77 1460.65   35.81
#Mann= 3 , 0 , 0
     -55     .11       0  781.93     .05       0  819.42     .11       0
#XS Ineff= 2 , 0
       0  773.31      34  821.82       0      34
Permanent Ineff=
       F       F
Bank Sta=781.93,819.42
XS Rating Curve= 0
Exp/Cntr=.5,.3

Type RM Length L Ch R = 1 ,16098.92,508.7,609.5,856.84
BEGIN DESCRIPTION:
461s6d - xs 1/4 of UP railroad spur
Bank Station offset =      4168
xsec 1/4 of UP Railroad Spur
Initially LOB and ROB extended using LIDAR data to ocntain 500 yr profile. No more high points found.
END DESCRIPTION:
XS GIS Cut Line= 6
 3220656.796250313864534.5013537     3220484.545    13864583.149
     3219963.372    13865017.621     3219946.126    13865059.428
     3219425.194    13865383.036 3219224.732314513865466.1410493
#Sta/Elev= 30
     -40    34.9   75.19   33.49  480.52   33.72  507.37   33.27  709.77   33.78
  780.67   32.34  800.26   34.78  817.23   32.35  826.91   26.68  829.07   24.35
  829.21   25.15  832.06   24.09   845.7   27.55  854.72   30.98  880.12    32.3
  898.74   32.02  924.83   33.15  955.72   33.01 1004.27   34.24 1031.52   33.36
 1272.74    33.1 1318.49   32.64 1389.13   33.13 1430.03   32.13 1477.31   33.27
 1509.78   27.64 1526.02   31.36 1556.06   33.44 1580.62   34.18    1693   35.35
#Mann= 5 ,-1 , 0
     -40     .13       0  817.23    .045       0  854.72     .13       0
 1477.31     .99       0 1556.06     .13       0
Bank Sta=817.23,854.72
XS Rating Curve= 0
Exp/Cntr=.3,.1

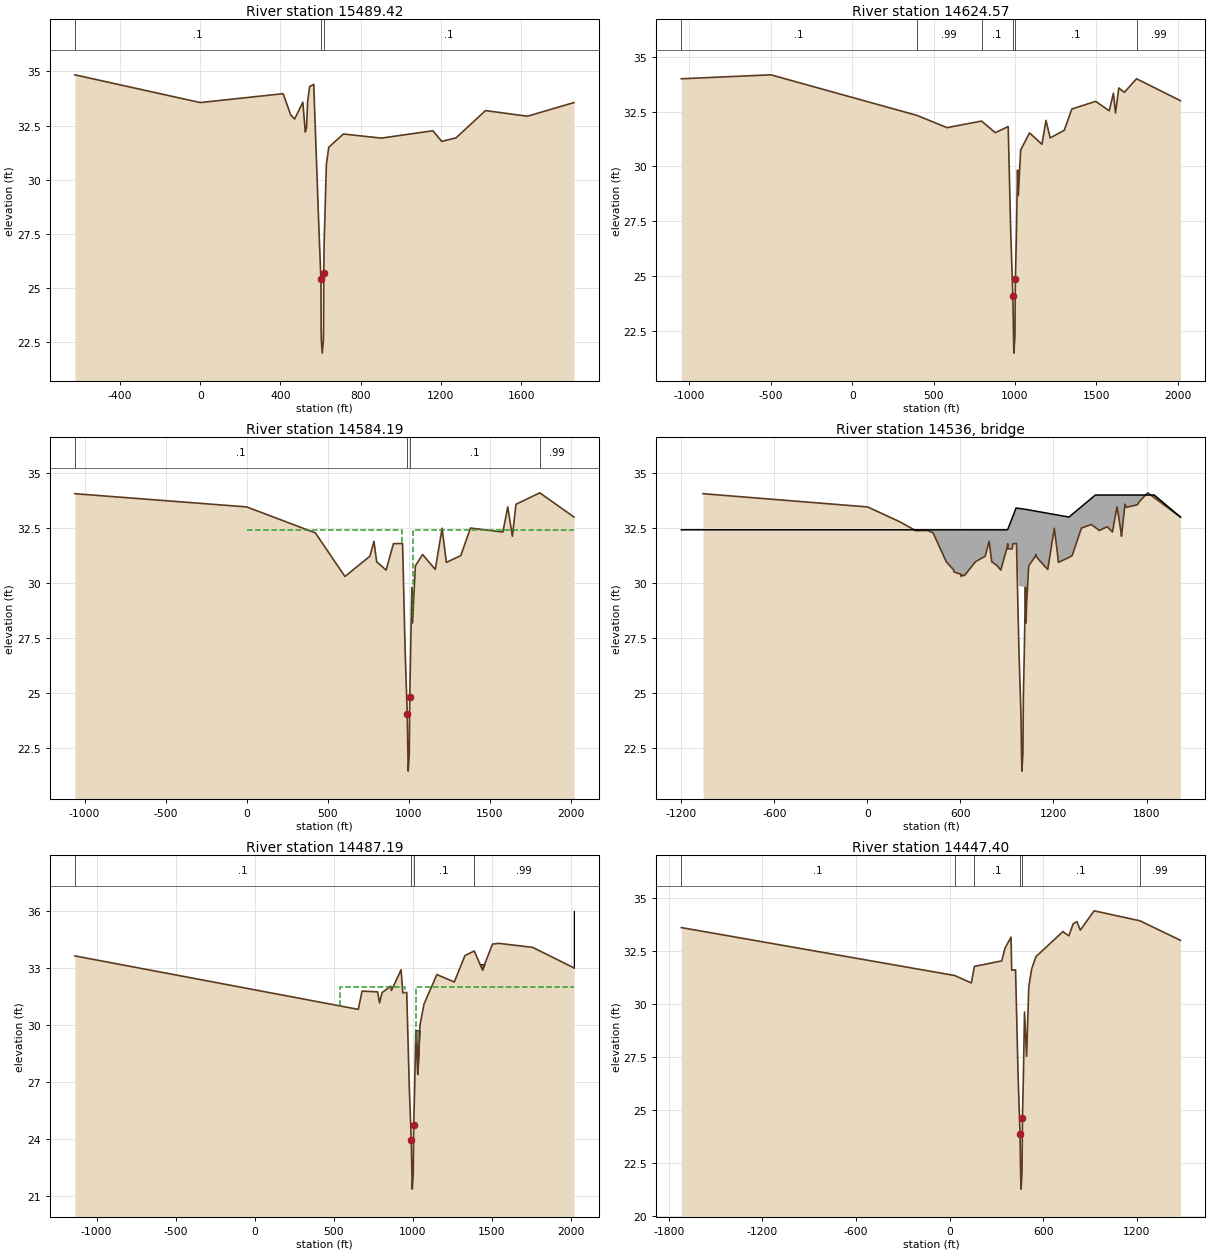
Type RM Length L Ch R = 1 ,15489.42,875.71,864.85,998.62
BEGIN DESCRIPTION:
461v11
Bank Station offset =      4392
LOB extended using LIDAR data to ocntain 500 yr profile. No high points found on ROB within watershed. ROB blocked at Watershed edge
LOB and ROB > channel reach length due to the fact that the floodplain contracting at structure. (Stream is more direct, OB are curved.)
END DESCRIPTION:
XS GIS Cut Line= 6
 3220817.771806613864390.5497142     3219603.888    13864574.397
     3219558.843      13864580.3     3219493.908    13864589.377
     3219195.817    13864635.798     3218418.098    13864297.516
#Sta/Elev= 30
    -625   34.84       0   33.56  413.22   33.97  451.17   32.99  470.62    32.8
   511.6   33.58  523.91    32.2  529.91    32.4  535.41    33.6  545.41    34.3
  565.91    34.4  591.91    27.7  601.91    25.4  602.91    23.1  603.91    22.6
  608.41      22  613.91    22.6  614.91    23.1  615.91    25.7  617.91    27.1
  628.91    30.7  640.91    31.5  713.72   32.11  903.02   31.92 1159.86   32.26
 1204.07   31.77 1275.02   31.93 1422.22   33.19 1631.53   32.93 1863.51   33.56
#Mann= 3 , 0 , 0
    -625      .1       0  601.91     .04       0  615.91      .1       0
#Block Obstruct= 2 , 0
       0                    1672       0      36
Bank Sta=601.91,615.91
XS Rating Curve= 0
Exp/Cntr=.3,.1

Type RM Length L Ch R = 1 ,14624.57,40.7,40.37,40.02
BEGIN DESCRIPTION:
461s5u - xs 4/4 of South Battlebell Road
Bank Station offset =      4007
No high points found on LOB and ROB
ROB Extended and blocked at watershed boundry.
END DESCRIPTION:
XS GIS Cut Line= 6
 3221610.438540113864257.4173396     3220111.133    13863719.535
      3219666.76    13863722.057     3219633.666    13863720.142
     3219625.027    13863720.393 3218637.101820113863728.4078444
#Sta/Elev= 30
   -1050      34    -500   34.18  397.58   32.33  582.63   31.77  794.88   32.07
  879.27   31.54  958.41   31.82  974.42    26.9  987.16   24.08  993.17   21.48
  999.83   22.26 1002.67   24.85  1008.5   26.75 1015.84   29.83  1020.4   28.67
 1035.09   30.75 1089.76   31.53 1165.95   31.01 1190.59    32.1 1216.41    31.3
 1303.04   31.65 1349.58   32.62 1495.88   32.97 1579.32   32.54  1605.1   33.34
 1617.94   32.44 1638.05   33.58 1672.21   33.38 1747.19      34    2017      33
#Mann= 6 ,-1 , 0
   -1050      .1       0  397.58     .99       0  794.88      .1       0
  987.16     .04       0 1002.67      .1       0 1747.19     .99       0
#Block Obstruct= 2 , 0
       0                    2015       0      36
Bank Sta=987.16,1002.67
XS Rating Curve= 0
Exp/Cntr=.5,.3

Type RM Length L Ch R = 1 ,14584.19,123.05,97,97.55
BEGIN DESCRIPTION:
Copy of 461s5u - xs 3/4 of South Battlebell Road
Bank Station offset =      4004
No more high points found on LOB and ROB to extend cross section.
LOB and ROB > channel reach length due to the fact that the floodplain contracting at structure. (Stream is more direct, OB are curved.)
ROB Extended and blocked at watershed boundary.
END DESCRIPTION:
XS GIS Cut Line= 6
 3221622.716709213864229.1061415      3220103.53    13863679.565
     3219679.397     13863681.27     3219666.375    13863682.146
     3219650.724    13863679.517 3218640.350801713863688.3810639
#Sta/Elev= 30
   -1060   34.06       0   33.46  423.76   32.28  605.88    30.3  759.86   31.22
  785.07    31.9  801.72   30.97  860.07   30.59  905.07   31.79  961.51    31.8
  977.52   26.88  990.26   24.06  996.27   21.46 1002.93   22.24 1005.77   24.83
 1018.94   29.81 1023.18   28.19 1040.34   30.78 1084.88    31.3 1163.19   30.62
 1205.34   32.49 1231.65   30.94 1320.57   31.25 1380.42    32.5 1580.36   32.32
 1610.36   33.46 1638.81   32.13 1661.22   33.58    1808    34.1    2019      33
#Mann= 4 ,-1 , 0
   -1060      .1       0  990.26     .04       0 1005.77      .1       0
    1808     .99       0
#XS Ineff= 2 , 0
       0     955   32.42    1025       0   32.42
Permanent Ineff=
       F       F
#Block Obstruct= 2 , 0
       0                    2017       0      36
Bank Sta=990.26,1005.77
XS Rating Curve= 0
Exp/Cntr=.5,.3

Type RM Length L Ch R = 3 ,14536   ,,,
BEGIN DESCRIPTION:
461s5, South Battlebell Road concrete bridge
END DESCRIPTION:
Bridge Culvert--1,0,-1,-1, 0
Deck Dist Width WeirC Skew NumUp NumDn MinLoCord MaxHiCord MaxSubmerge Is_Ogee
30,37.2,2.6,0, 13, 13, , , .95, 0, 0,0,,
   -1200       0  903.94  944.23   958.6  958.62  959.42 1019.31    1020    1300
    1470    1850    2019
   32.42   32.42   32.42   33.14   33.41   33.41   33.41   33.35   33.35      33
      34      34      33
                                           29.88   29.88   29.82
                        
 -662.47  537.53  904.47  944.76  959.13  959.15  959.95 1019.84 1019.88 1297.53
 1467.53 1847.53 2019.53
   32.42   32.42   32.42   33.14   33.41   33.41   33.41   33.35   33.35      33
      34      34      33
                                           29.88   29.88   29.82
                        
BR Coef=-1 , 0 , 0 ,, 0 ,,,.7,0,,0,
WSPro=,,,, 1 ,,,, 0 ,,,, 0 ,,,,-1 ,-1 ,-1 , 0 , 0 , 0 , 0 , 0
BR U #Sta/Elev= 72
   -1060   34.06       0   33.46   10.68   33.43  213.28   32.77  311.87   32.38
   384.9   32.39  388.67   32.39  423.76   32.28  509.26   30.96  555.08   30.61
  555.53    30.6  558.76    30.5  600.17   30.41  605.88    30.3   607.5   30.36
  626.21   30.34  696.95   30.97  759.86   31.22  785.07    31.9  801.72   30.97
  835.31    30.8  860.07   30.59  901.35   31.62  905.07   31.79   906.3   31.56
  933.96   31.55  936.18   31.61  936.71   31.78  961.51    31.8  977.52   26.88
  990.26   24.06  992.09    23.3  993.06   22.62  996.27   21.46 1002.93   22.24
 1004.23   23.38 1005.77   24.83  1011.6   26.73 1018.94   29.81 1023.18   28.19
 1025.87   28.88 1026.36      29 1034.52   30.04 1040.34   30.78 1083.23   31.22
 1084.88    31.3 1087.18    31.3 1092.03   31.17 1149.04   30.72 1163.19   30.62
 1174.68   31.13 1205.34   32.49 1225.52   31.36 1231.65   30.94 1298.51   31.16
 1320.57   31.25 1380.42    32.5 1444.48   32.66 1496.18   32.39 1545.78   32.56
 1580.36   32.32 1607.51   33.38 1610.36   33.46 1634.24   32.38 1638.81   32.13
 1643.49   32.43 1661.22   33.58 1670.88   33.44 1742.51   33.56 1752.66   33.69
    1808    34.1    2019      33
BR U #Mann= 4
   -1060      .1  990.26    .035 1005.77      .1    1808     .99
BR D #Sta/Elev= 47
-1137.47   33.63  537.53   31.21   655.1   30.82  678.98   31.78  752.53   31.76
  777.24   31.74  781.59   31.54  789.69   31.16  805.33    31.7  860.64   32.04
  864.69   31.81   870.8    31.9  889.45   32.41  925.93    32.9  936.71   31.69
  961.51   31.71  977.52   26.79  990.26   23.97  992.09   23.21  993.06   22.53
  996.27   21.37 1002.93   22.15 1004.23   23.29 1005.77   24.74  1011.6   26.64
 1018.94   29.72 1031.03   27.41 1035.53   28.24 1039.67      29 1044.95   29.97
  1062.9   30.74 1070.94    31.1 1139.77   32.54 1152.19   32.65 1169.75   32.75
 1262.45   32.26 1329.96   33.65  1388.7   33.89 1440.28    32.9 1451.95   33.03
 1504.43   34.25 1544.55   34.29 1554.97   34.28 1557.01   34.26 1672.58    34.1
 1757.82   34.08 2019.53      33
BR D #Mann= 4
-1137.47      .1  990.26    .035 1005.77      .1  1388.7     .99
BC Design=,, 0 ,, 0 ,,,,,,

Type RM Length L Ch R = 1 ,14487.19,84.42,39.79,40.02
BEGIN DESCRIPTION:
Copy of 461s5u - xs 2/4 of South Battlebell Road
Bank Station offset =      4541
LOB extended using LIDAR data
LOB and ROB > channel reach length due to the fact that the floodplain contracting at structure. (Stream is more direct, OB are curved.)
ROB Extended and blocked at watershed boundry.
END DESCRIPTION:
XS GIS Cut Line= 6
 3221801.124481913863575.2445448     3219678.858    13863583.771
     3219665.836    13863584.648     3219650.185    13863582.018
     3219624.266    13863582.895 3218644.4416512 13863590.844135
#Sta/Elev= 30
-1137.47   33.63   655.1   30.82  678.98   31.78  777.24   31.74  789.69   31.16
  805.33    31.7  860.64   32.04  864.69   31.81  925.93    32.9  936.71   31.69
  961.51   31.71  977.52   26.79  990.26   23.97  996.27   21.37 1002.93   22.15
 1005.77   24.74  1011.6   26.64 1018.94   29.72 1031.03   27.41 1044.95   29.97
 1070.94    31.1 1152.19   32.65 1262.45   32.26 1329.96   33.65  1388.7   33.89
 1440.28    32.9 1504.43   34.25 1544.55   34.29 1757.82   34.08 2019.53      33
#Mann= 4 ,-1 , 0
-1137.47      .1       0  990.26     .04       0 1005.77      .1       0
  1388.7     .99       0
#XS Ineff= 2 , 0
  537.53  952.53      32 1022.53  537.53      32
Permanent Ineff=
       F       F
#Block Obstruct= 3 ,-1
 1018.94 1044.95   29.72 2017.53 2019.53      36    1419    1464    33.2
Bank Sta=990.26,1005.77
XS Rating Curve= 0
Exp/Cntr=.5,.3

Type RM Length L Ch R = 1 ,14447.40,822.26,738.69,722.23
BEGIN DESCRIPTION:
Copy of 461s5u - xsec 1/4 of South Battlebell Road
Bank Station offset =      4542
LOB extended using LIDAR data to contain 500 yr profile
ROB Extended and blocked at watershed boundry.
END DESCRIPTION:
XS GIS Cut Line= 6
 3221845.9021186 13863535.064738     3219678.637    13863543.772
     3219665.615    13863544.648     3219649.963    13863542.019
     3219624.045    13863542.896  3218646.21057613863550.8289911
#Sta/Elev= 30
   -1720    33.6   32.87   31.34  139.52   30.99  158.97   31.77  334.46   32.03
   355.1   32.63  393.88   33.15  397.96   31.59  422.76   31.61  438.77   26.69
  451.51   23.87  454.31   22.43  457.52   21.27  464.18   22.05  467.02   24.64
  472.85   26.54  480.19   29.62  493.49   27.53   507.2   30.71  509.32    30.9
  526.52   31.66  553.54   32.23  726.17   33.41  764.38   33.21  792.21   33.78
  816.42   33.88  837.68   33.48  926.45   34.39 1220.28   33.92    1480      33
#Mann= 6 ,-1 , 0
   -1720      .1       0   32.87     .99       0  158.97      .1       0
  451.51     .04       0  467.02      .1       0 1220.28     .99       0
#Block Obstruct= 2 , 0
       0                    1478       0      36
Bank Sta=451.51,467.02
XS Rating Curve= 0
Exp/Cntr=.3,.1

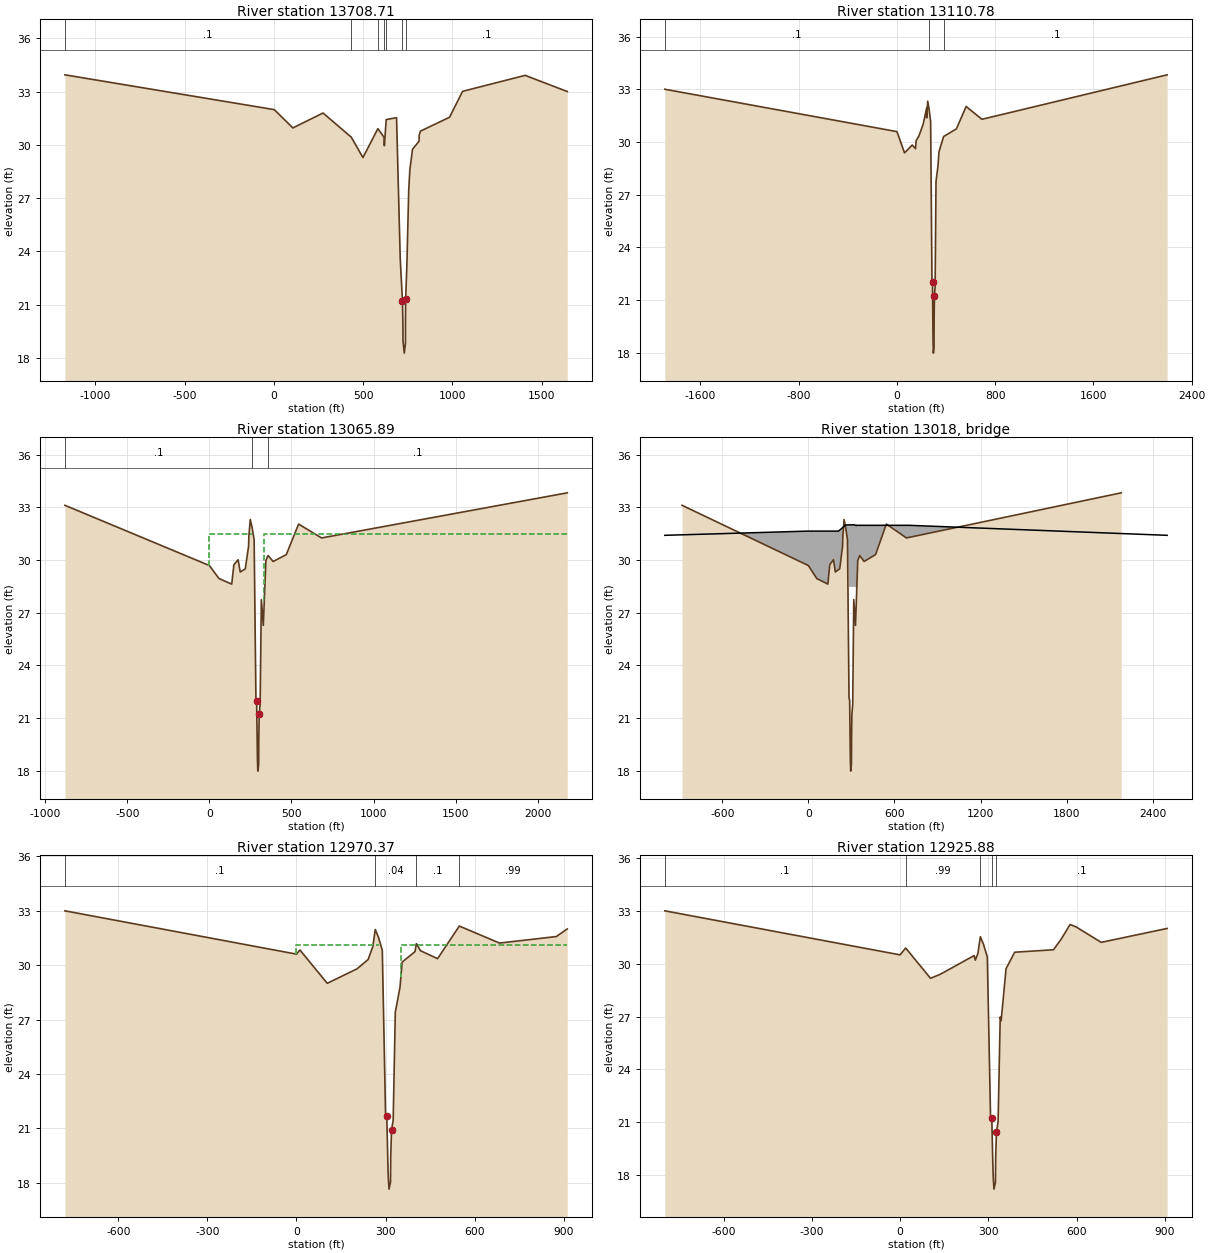
Type RM Length L Ch R = 1 ,13708.71,647.97,597.93,617.98
BEGIN DESCRIPTION:
461v10
Bank Station offset =      4269
LOB extended using LIDAR data to contain 500 yr profile
LOB and ROB > channel reach length due to the fact that the floodplain contracting at structure. (Stream is more direct, OB are curved.)
ROB Extended and blocked at watershed boundry.
END DESCRIPTION:
XS GIS Cut Line= 6
 3221557.874603313862849.3566339     3220389.511    13862787.498
     3219977.836    13862765.702     3219672.226    13862807.101
     3218991.241    13862899.912 3218757.3334497 13862931.791107
#Sta/Elev= 30
   -1170   33.94    2.87   31.98  107.02   30.95  275.91   31.79  434.21   30.43
   499.5   29.28  583.14   30.91  617.44   30.43  619.45   29.95   629.8   31.42
  687.76   31.53  708.38   23.58  720.86   21.21  723.28   19.96  723.84   18.97
  730.92   18.27  737.47    18.8  737.64   20.08  738.91   21.34  745.42   23.17
  755.92   27.45  762.08   28.57  777.14   29.75  813.69    30.2  814.78   30.55
  821.47   30.77  984.47   31.55 1057.68   33.01 1407.93   33.91    1644      33
#Mann= 7 ,-1 , 0
   -1170      .1       0  434.21     .99       0  583.14      .1       0
  617.44     .99       0   629.8      .1       0  720.86     .04       0
  738.91      .1       0
#Block Obstruct= 2 , 0
       0                    1642       0      36
Bank Sta=720.86,738.91
XS Rating Curve= 0
Exp/Cntr=.3,.1

Type RM Length L Ch R = 1 ,13110.78,40.28,44.88,47.38
BEGIN DESCRIPTION:
461s4u - xsec 4/4 of Jones Road
Bank Station offset =      4703
LOB and ROB extended using LIDAR data.
ROB Extended and blocked at watershed boundry.
Set n = 0.04 along the width of bridge opening due to light weeds and grass as only vegetation.
END DESCRIPTION:
XS GIS Cut Line= 6
  3221723.51502713862292.9979362     3219673.192     13862204.69
     3219593.863    13862207.449     3219517.983    13862228.834
     3219139.766    13862210.055      3217647.05     13862171.61
#Sta/Elev= 30
   -1890      33       0   30.59   61.82   29.38  124.41   29.83  150.89   29.62
  156.43   30.08  178.28   30.33  213.81   31.02  241.62   31.93  242.19   31.37
   250.6   32.32  261.47   31.88  274.24   31.17  285.11   22.17  289.46   22.01
  292.95   19.42  294.32   18.67  296.82   17.99  301.88   18.38  302.65   19.83
  305.22   21.24  310.82    21.8  318.06   27.76  333.35   28.59  342.43   29.45
  379.99   30.31  484.37   30.75  563.34   32.02  692.09   31.29    2200   33.82
#Mann= 3 ,-1 , 0
   -1890      .1       0  261.47     .04       0  379.99      .1       0
#Block Obstruct= 2 , 0
       0                     942       0      36
Bank Sta=289.46,305.22
XS Rating Curve= 0
Exp/Cntr=.5,.3

Type RM Length L Ch R = 1 ,13065.89,99.06,95.52,95.32
BEGIN DESCRIPTION:
Copy of 461s4u - xsec 3/4 of Jones Road
Bank Station offset =      4705
LOB and ROB extended using LIDAR data. ROB Extended and blocked at watershed boundry.
Set n = 0.04 along the width of bridge opening due to light weeds and grass as only vegetation.
END DESCRIPTION:
XS GIS Cut Line= 6
     3220708.194    13862173.726     3219731.317    13862173.726
     3219589.635    13862176.753     3219508.501    13862180.386
     3219388.011    13862180.992      3217658.44     13862151.12
#Sta/Elev= 30
    -880   33.11       0   29.68   58.49   28.94  136.13   28.62  149.23   29.72
  174.96   30.01  188.06   29.31  218.65   29.49   238.6   30.77  240.58   31.35
  248.99    32.3  259.86   31.86  272.63   31.15   283.5   22.15  287.85   21.99
  292.71   18.65  295.21   17.97  300.27   18.36  301.04   19.81  303.61   21.22
  309.21   21.78  316.45   27.74  328.45   26.27  344.34   29.96  357.63   30.25
  388.25   29.91   468.4    30.3  543.52   32.04  683.64   31.25    2180   33.82
#Mann= 3 ,-1 , 0
    -880      .1       0  259.86     .04       0  357.63      .1       0
#XS Ineff= 2 , 0
       0   259.8    31.5  334.55       0    31.5
Permanent Ineff=
       F       F
#Block Obstruct= 2 , 0
       0                     922       0      36
Bank Sta=287.85,303.61
XS Rating Curve= 0
Exp/Cntr=.5,.3

Type RM Length L Ch R = 3 ,13018   ,,,
BEGIN DESCRIPTION:
461s4, Jones Road concrete bridge
END DESCRIPTION:
Bridge Culvert--1,0,-1,-1, 0
Deck Dist Width WeirC Skew NumUp NumDn MinLoCord MaxHiCord MaxSubmerge Is_Ogee
30,37.2,2.6,0, 12, 12, 31.57, , .95, 0, 0,0,,
   -1000       0  210.03   244.7   259.7   259.8  319.47  334.55   334.6  371.91
     700    2500
    31.4   31.64   31.64   31.88   31.99   31.99      32   31.95   31.97   31.97
   31.97    31.4
                                           28.46   28.47   28.42
                
   -1000       0  227.03   261.7   276.7   276.8  336.47  351.55   351.6  388.91
     700    2500
    31.4   31.64   31.64   31.88   31.99   31.99      32   31.95   31.95   31.97
   31.97    31.4
                                           28.46   28.47   28.42
                
BR Coef=-1 , 0 , 0 ,, 0 ,,,.8,0,,0,
WSPro=,,,, 1 ,,,, 0 ,,,, 0 ,,,,-1 ,-1 ,-1 , 0 , 0 , 0 , 0 , 0
BC Design=,, 0 ,, 0 ,,,,,,

Type RM Length L Ch R = 1 ,12970.37,45.55,44.5,44.33
BEGIN DESCRIPTION:
Copy of 461s4u - xsec 2/4 of Jones Road
Bank Station offset =      4688
LOB and ROB extended using LIDAR data to contain 500 yr profile. Set n = 0.04 along the width of bridge opening due to light weeds and grass as only vegetation.
n=0.99 used for ineffective areas on ROB
ROB Extended and blocked at watershed boundary.
END DESCRIPTION:
XS GIS Cut Line= 6
     3220607.608    13862079.228     3219730.731    13862079.228
     3219589.049    13862082.255     3219507.915    13862085.888
     3219387.425    13862086.494 3218915.770642213862080.6264665
#Sta/Elev= 30
    -780      33       0   30.61    11.5   30.84  103.63      29  204.03    29.8
  241.12   30.31  256.99   31.02   265.4   31.97  276.27   31.53  289.04   30.82
  299.91   21.82  304.26   21.66  307.75   19.07  309.12   18.32  311.62   17.64
  316.68   18.03  317.45   19.48  320.02   20.89  325.62   21.45  332.86   27.41
   348.7   28.79  355.79   30.17  399.21   30.75  403.75   31.19  417.52    30.8
  475.18   30.36  548.46   32.16  683.73   31.22     875   31.58     912      32
#Mann= 4 ,-1 , 0
    -780      .1       0   265.4     .04       0  403.75      .1       0
  548.46     .99       0
#XS Ineff= 2 , 0
       0   276.8    31.1  351.55       0    31.1
Permanent Ineff=
       F       F
#Block Obstruct= 2 , 0
       0                     910       0      36
Bank Sta=304.26,320.02
XS Rating Curve= 0
Exp/Cntr=.5,.3

Type RM Length L Ch R = 1 ,12925.88,1268.92,1290.24,1349.68
BEGIN DESCRIPTION:
Copy of 461s4u - xsec 1/4 of Jones Road
Bank Station offset =      4681
ROB Extended and blocked at watershed boundry.
n=0.99 used for ineffective areas on LOB
END DESCRIPTION:
XS GIS Cut Line= 6
     3220627.335    13862035.229     3219730.458    13862035.229
     3219588.777    13862038.256     3219507.643    13862041.889
     3219387.153    13862042.494 3218919.498321213862036.6781451
#Sta/Elev= 30
    -800      33       0    30.5   18.99   30.89  103.35   29.17  136.95    29.4
  251.75   30.46  255.65    30.2  264.51   30.58  272.92   31.53  283.79   31.09
  296.56   30.38  307.43   21.38  311.78   21.22  315.27   18.63  316.64   17.88
  319.14    17.2   324.2   17.59  324.97   19.04  327.54   20.45  333.14   21.01
  340.38   26.97  343.48   26.75  360.18   29.71  389.49   30.65  521.41   30.79
  547.64   31.39  577.76   32.22  598.08   32.09  683.73   31.21     908      32
#Mann= 5 ,-1 , 0
    -800      .1       0   18.99     .99       0  272.92      .1       0
  311.78     .04       0  327.54      .1       0
#Block Obstruct= 2 , 0
       0                     906       0      36
Bank Sta=311.78,327.54
XS Rating Curve= 0
Exp/Cntr=.3,.1