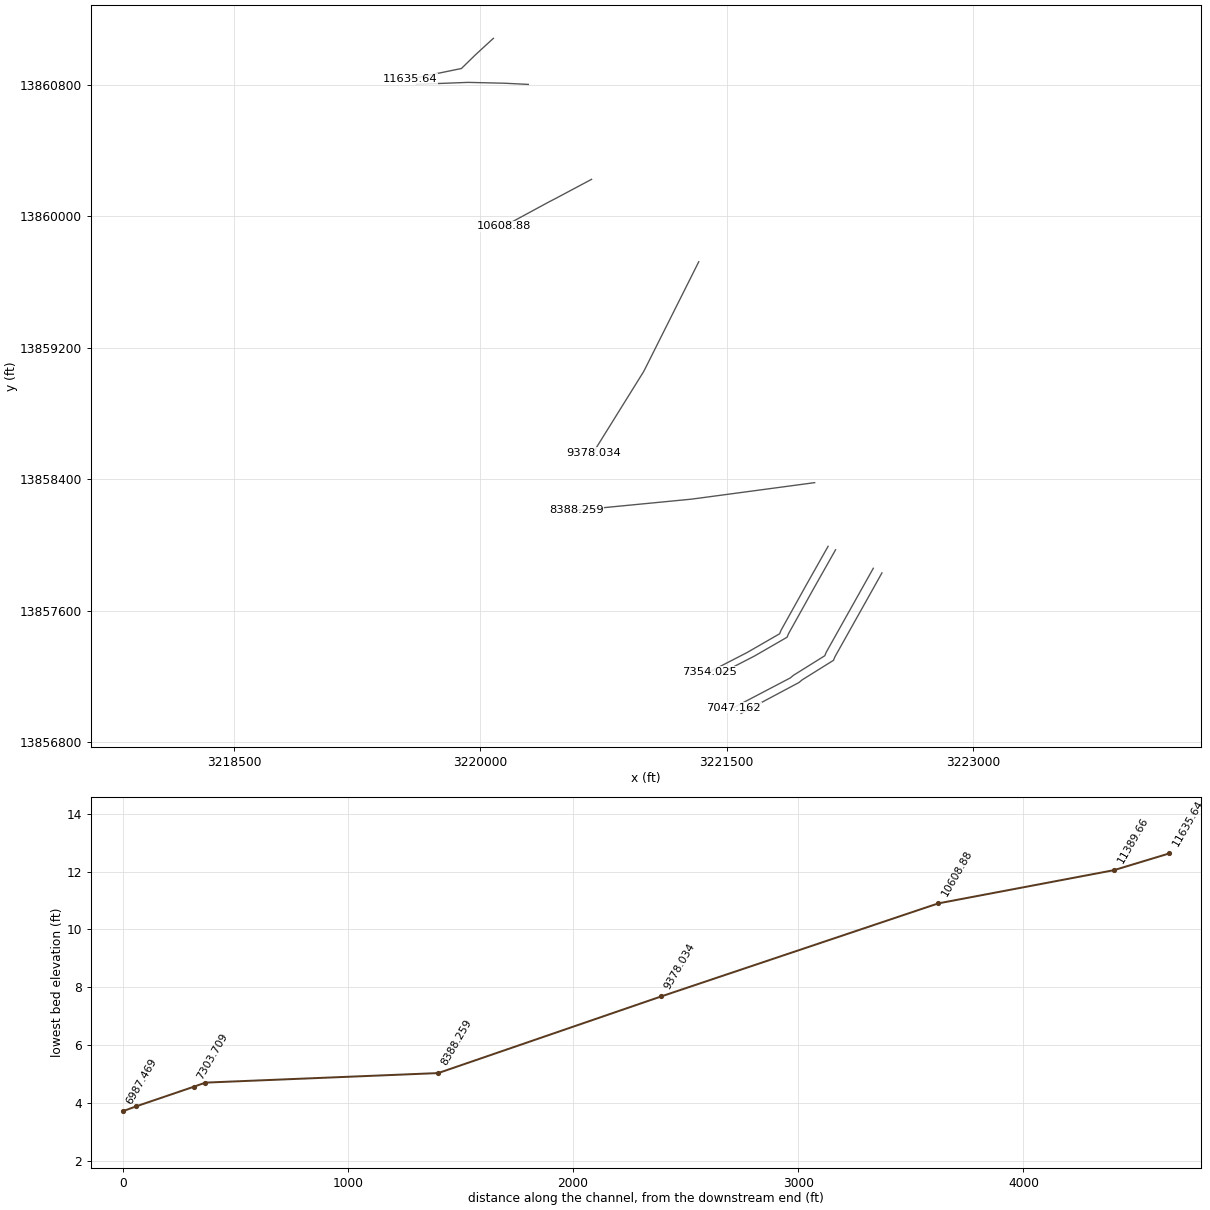
HEC-RAS study O200-00-00.prj: O200-00-00

--- O200-00-00.g04 (geometry) --- (continued)

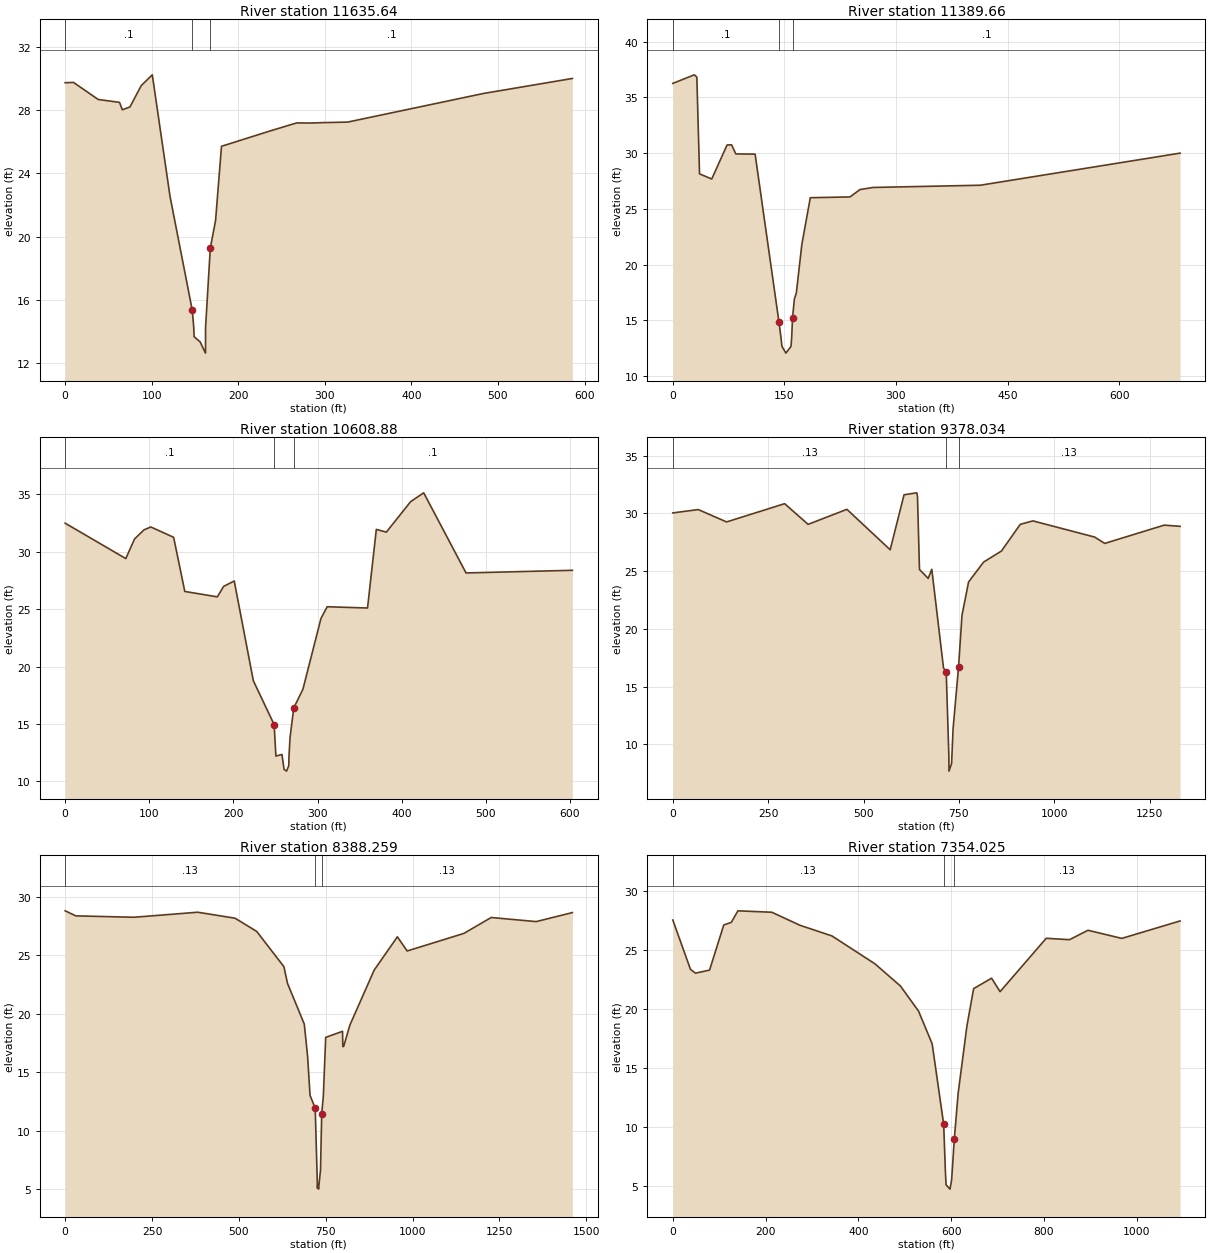
Type RM Length L Ch R = 1 ,11635.64,261.91,245.98,228.48
BEGIN DESCRIPTION:
461v9
Bank Station offset =      4838
END DESCRIPTION:
XS GIS Cut Line= 5
     3220080.001    13861084.479     3219971.871    13860985.149
     3219885.417     13860900.79     3219674.245    13860857.313
 3219573.576445113860836.5869247
#Sta/Elev= 25
       0   29.73    9.66   29.75   38.22   28.67   62.76   28.49   66.09   28.02
   74.91    28.2   87.89   29.55  100.67   30.23  121.14   22.55   146.9   15.33
  148.58   14.25  148.98   13.67  155.95   13.34  162.15   12.63  162.18   14.21
  167.69   19.27  173.79   21.02  180.62   25.71  238.48   26.71  267.62   27.19
  283.05   27.18   299.6   27.21  326.27   27.24  483.22   29.05     586      30
#Mann= 3 , 0 , 0
       0      .1       0   146.9     .04       0  167.69      .1       0
Bank Sta=146.9,167.69
XS Rating Curve= 0
Exp/Cntr=.3,.1

Type RM Length L Ch R = 1 ,11389.66,768.84,780.78,786.13
BEGIN DESCRIPTION:
461v8
Bank Station offset =      4848
END DESCRIPTION:
XS GIS Cut Line= 5
     3220292.846    13860803.982     3220150.506     13860811.09
     3219925.839    13860816.302     3219695.983    13860807.626
 3219611.303310413860804.4297337
#Sta/Elev= 25
       0   36.26    28.9   37.03    32.3   36.83   35.93   28.14   52.34   27.68
   72.92   30.73   78.99   30.75   84.71   29.93  110.67   29.91  142.75   14.83
  145.38   13.48  146.71   12.67     152   12.05  158.91   12.65  159.81   13.44
  160.96   15.22  163.44    16.9  166.08   17.45  173.46   21.79  184.84      26
  238.19   26.07  251.68   26.73  269.12   26.92  413.39   27.12     682      30
#Mann= 3 , 0 , 0
       0      .1       0  142.75     .04       0  160.96      .1       0
Bank Sta=142.75,160.96
XS Rating Curve= 0
Exp/Cntr=.3,.1

Type RM Length L Ch R = 1 ,10608.88,1209,1230.86,1254.94
BEGIN DESCRIPTION:
461v7
Bank Station offset =      4737
END DESCRIPTION:
XS GIS Cut Line= 4
     3220677.765    13860226.001     3220458.505    13860109.158
     3220420.297    13860089.522     3220146.482    13859941.249
#Sta/Elev= 30
       0   32.47   72.07   29.39   82.51    31.1   93.74   31.89  101.78   32.14
  128.93   31.24  142.19   26.53  180.84   26.06   188.3   26.97  200.94   27.44
  223.61   18.77  248.35   14.95  250.45   12.21  257.68   12.35  260.15   11.05
  263.11    10.9  265.73   11.37  265.94    12.1   267.2   13.78  271.67    16.4
  282.54   18.02  304.01   24.18  311.38    25.2  359.33   25.09  369.79   31.93
  381.72   31.69  410.51   34.34   426.1   35.11   476.4   28.14  602.79   28.37
#Mann= 3 , 0 , 0
       0      .1       0  248.35     .04       0  271.67      .1       0
Bank Sta=248.35,271.67
XS Rating Curve= 0
Exp/Cntr=.3,.1

Type RM Length L Ch R = 1 ,9378.034,1030,989.78,926.26
BEGIN DESCRIPTION:
461v6
Bank Station offset =      4276
END DESCRIPTION:
XS GIS Cut Line= 6
     3221330.541    13859724.189     3221011.738     13859088.37
     3221009.555    13859084.111     3221000.601    13859066.094
     3220994.595    13859054.848     3220687.706    13858561.549
#Sta/Elev= 30
       0   30.04   66.73   30.33     141   29.26  293.22   30.84  354.68   29.05
  456.48   30.35  569.89   26.85  606.26   31.61  639.73   31.78   641.5   31.46
  646.72   25.14  669.65   24.37  679.02   25.16  709.74   16.61  716.81   16.28
  723.83    8.91  724.03    7.68  730.93    8.34  734.71   11.31  749.07   16.67
  758.15   21.17  775.44   24.06  814.74   25.78  861.62   26.74  910.99   29.05
  944.03   29.35 1105.85   27.95 1132.46    27.4 1288.15   28.98 1329.89   28.88
#Mann= 3 , 0 , 0
       0     .13       0  716.81     .06       0  749.07     .13       0
Bank Sta=716.81,749.07
XS Rating Curve= 0
Exp/Cntr=.3,.1

Type RM Length L Ch R = 1 ,8388.259,981.88,1034.23,1043.22
BEGIN DESCRIPTION:
461v5
Bank Station offset =      4271
END DESCRIPTION:
XS GIS Cut Line= 4
     3222036.265    13858379.265     3221328.181    13858284.288
     3221281.373     13858278.26     3220586.477    13858210.838
#Sta/Elev= 30
       0    28.8   30.52   28.37  197.78   28.25  381.56   28.68  489.02   28.17
  551.33   27.04  629.56   24.03  640.09   22.59  688.15   19.13  697.73   16.38
  704.77   13.04  719.67   11.93  726.18     5.1  726.82    5.43  729.22    5.03
  734.87    6.65  738.34   11.45  743.03   12.98  749.83   17.99  798.31   18.51
  799.14    17.2   801.6   17.22  819.28   19.03  889.39   23.74  956.13   26.58
  984.29   25.37 1147.44   26.87 1226.18   28.23 1355.53   27.88 1459.78   28.65
#Mann= 3 , 0 , 0
       0     .13       0  719.67     .06       0  738.34     .13       0
Bank Sta=719.67,738.34
XS Rating Curve= 0
Exp/Cntr=.3,.1

Type RM Length L Ch R = 1 ,7354.025,49.94,50.32,52.54
BEGIN DESCRIPTION:
461s3u - xs 4/4 of Lynchburg Reservoir Channel
Bank Station offset =      4403
END DESCRIPTION:
XS GIS Cut Line= 6
      3222118.01    13857991.488      3221986.65    13857759.002
     3221831.486    13857480.314      3221822.71    13857459.063
     3221624.095    13857344.469     3221397.332    13857227.767
#Sta/Elev= 30
       0   27.54   38.11   23.35   48.84   23.03   79.23   23.29  109.82   27.12
   126.1   27.34  140.32   28.32  213.34    28.2  274.32   27.09  342.97   26.19
  435.76   23.82  490.62   21.94   529.8    19.8  559.05   17.03  583.84    10.2
  587.51    6.22  588.98    5.07   597.5     4.7  601.04    5.51  606.73    8.95
  615.07   12.85  633.93   18.54  648.41   21.72  687.14    22.6  705.42   21.46
  804.89   25.99  855.01   25.87  894.91   26.67  967.76   25.98 1093.33   27.46
#Mann= 3 ,-1 , 0
       0     .13       0  583.84     .06       0  606.73     .13       0
Bank Sta=583.84,606.73
XS Rating Curve= 0
Exp/Cntr=.5,.3

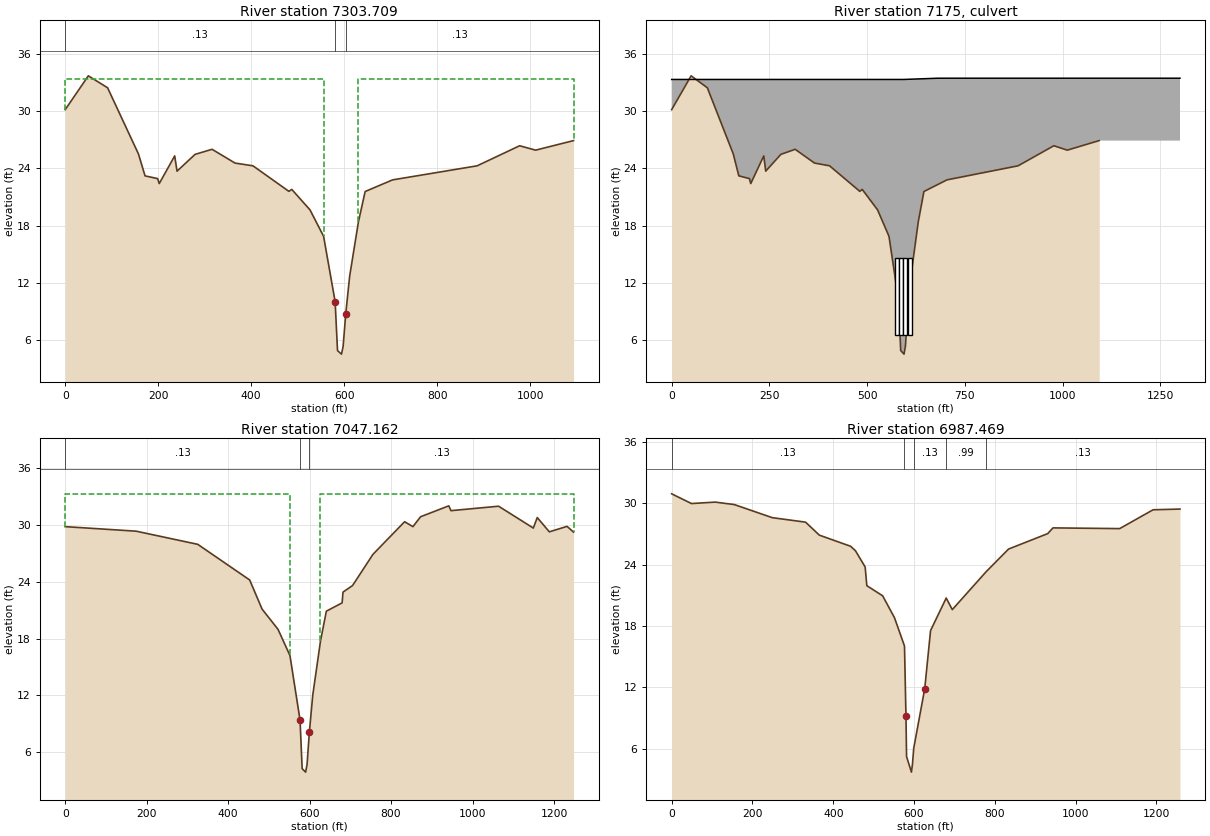
Type RM Length L Ch R = 1 ,7303.709,256.62,256.55,254.86
BEGIN DESCRIPTION:
Copy of 461s3u - xs 3/4 of Lynchburg Reservoir Channel
Bank Station offset =      4406
END DESCRIPTION:
XS GIS Cut Line= 6
      3222163.46    13857970.459       3222032.1    13857737.973
     3221876.936    13857459.285      3221868.16    13857438.034
     3221669.545     13857323.44     3221442.782    13857206.738
#Sta/Elev= 30
       0   30.15   49.75   33.69   91.16   32.44  157.57   25.51  171.72   23.22
  198.89   22.93  202.22   22.41  235.54   25.31  240.53   23.71  279.36   25.47
  315.82      26   365.2   24.56  403.85   24.27  481.06    21.6  487.34    21.8
  526.52   19.66  555.77   16.89  580.56   10.06   585.7    4.93  594.22    4.56
  597.76    5.37  603.45    8.81  611.79   12.71  630.65    18.4  645.13   21.58
  704.18    22.8  886.01   24.27  977.37   26.37 1011.79   25.91 1093.33   26.91
#Mann= 3 , 0 , 0
       0     .13       0  580.56     .06       0  603.45     .13       0
#XS Ineff= 2 , 0
       0  555.77   33.31  630.65       0   33.31
Permanent Ineff=
       F       F
Bank Sta=580.56,603.45
XS Rating Curve= 0
Exp/Cntr=.5,.3

Type RM Length L Ch R = 2 ,7175    ,,,
BEGIN DESCRIPTION:
461s3, Lynchburg Reservoir Channel
END DESCRIPTION:
Bridge Culvert--1,0,-1,-1, 0
Deck Dist Width WeirC Skew NumUp NumDn MinLoCord MaxHiCord MaxSubmerge Is_Ogee
101.5,125,2.6,0, 6, 6, , , .95, 0, 0,0,,
       0     394  532.89  593.28  680.17    1300
   33.31   33.31   33.31   33.31   33.44   33.44
                                                
       0     390  528.89  589.28  676.17    1300
   33.31   33.31   33.31   33.31   33.44   33.44
                                                
BR Coef=-1 , 0 , 0 ,, 0 ,,,.8,0,,0,
WSPro=,,,, 1 ,,,, 0 ,,,, 0 ,,,,-1 ,-1 ,-1 , 0 , 0 , 0 , 0 , 0
Multiple Barrel Culv=2,8,10,211.66,.015,.5,1,10,1,6.58,5.73, 4,Culvert #1  , 0 ,22.445
   575.5   571.5   586.5   582.5   597.5   593.5   608.5   604.5
Culvert Bottom n=.015
BC Design=,, 0 ,, 0 ,,,,,,

Type RM Length L Ch R = 1 ,7047.162,60.04,59.69,57.04
BEGIN DESCRIPTION:
Copy of 461s3u - xs 2/4 of Lynchburg Reservoir Channel
Bank Station offset =      4410
END DESCRIPTION:
XS GIS Cut Line= 6
     3222393.126    13857857.714     3222106.602     13857346.54
     3222097.826    13857325.289     3221906.546    13857205.881
     3221888.451     13857190.57     3221543.194    13857009.622
#Sta/Elev= 30
       0   29.84  174.13   29.36  325.36   27.97  452.93    24.2  483.35   21.12
  522.53   18.98  551.78   16.21  576.57    9.38  581.71    4.25  590.23    3.88
  593.77    4.69  599.46    8.13   607.8   12.03  626.66   17.72  641.14    20.9
  679.87   21.78  682.05   22.92  705.47   23.61  755.55   26.91  833.29   30.36
  853.68   29.84  872.64   30.89  941.78   32.04  947.05   31.53 1064.01      32
 1149.31   29.69 1158.91    30.8 1188.58   29.29 1232.12   29.87 1247.99   29.26
#Mann= 3 , 0 , 0
       0     .13       0  576.57     .06       0  599.46     .13       0
#XS Ineff= 2 , 0
       0  551.78   33.31  626.66       0   33.31
Permanent Ineff=
       F       F
Bank Sta=576.57,599.46
XS Rating Curve= 0
Exp/Cntr=.5,.3

Type RM Length L Ch R = 1 ,6987.469,203.3,198.97,205.89
BEGIN DESCRIPTION:
Copy of 461s3u - xs 1/4 of Lynchburg Reservoir Channel
Bank Station offset =      4410
LOB and ROB > channel reach length due to the fact that the floodplain contracting at structure. (Stream is more direct, OB are curved.) VERY CLOSE to channel length here.
END DESCRIPTION:
XS GIS Cut Line= 6
     3222445.979    13857829.845     3222159.455    13857318.672
      3222150.68    13857297.421       3221959.4    13857178.012
     3221941.305    13857162.701     3221588.166    13856974.427
#Sta/Elev= 30
       0   30.92   48.98   29.97  107.86   30.11  155.11   29.87  248.93   28.59
  331.51   28.15  365.59   26.88  443.07   25.79  455.09   25.35  478.96   23.77
  483.12   21.94   522.3   20.95  551.55   18.81  576.34   16.04  580.01    9.21
  581.48    5.23  593.54    3.71  596.14    4.52  599.23    6.05  626.43   11.86
  640.91   17.55  679.64   20.73  694.71    19.6  777.89   23.28  833.97   25.52
  930.92   27.03  943.98   27.59 1109.07   27.52 1191.77   29.36 1258.38   29.43
#Mann= 5 ,-1 , 0
       0     .13       0  576.34     .06       0  599.23     .13       0
  679.64     .99       0  777.89     .13       0
Bank Sta=580.01,626.43
XS Rating Curve= 0
Exp/Cntr=.3,.1