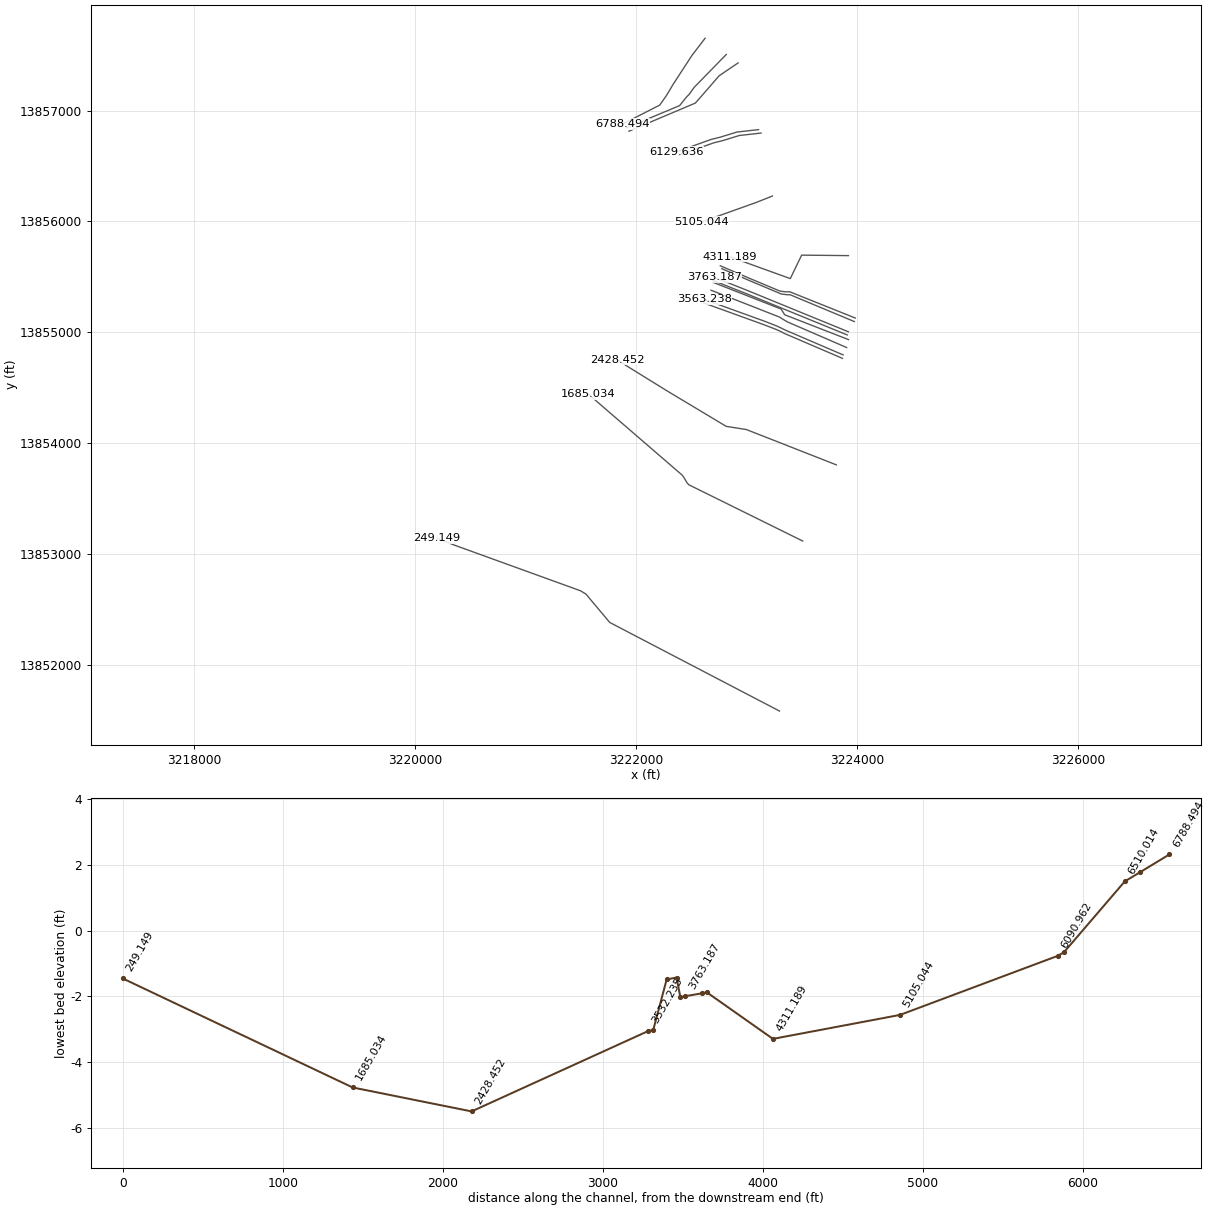
HEC-RAS study O200-00-00.prj: O200-00-00

--- O200-00-00.g04 (geometry) --- (continued)

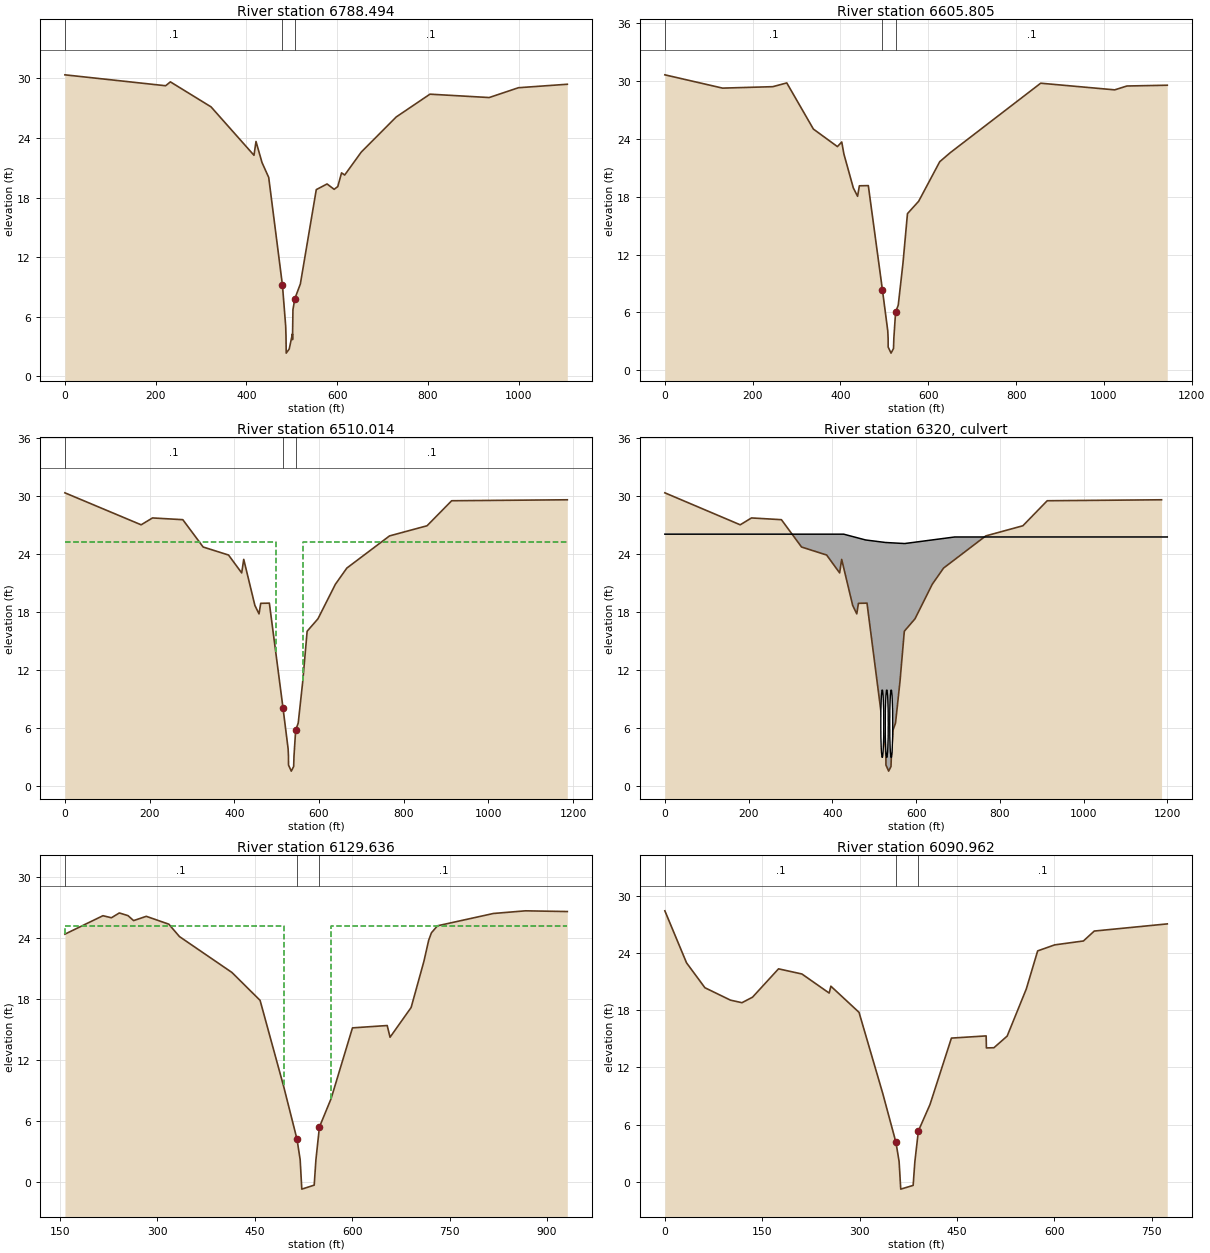
Type RM Length L Ch R = 1 ,6788.494,186.14,182.69,172.92
BEGIN DESCRIPTION:
461v4
Bank Station offset =      4512
END DESCRIPTION:
XS GIS Cut Line= 6
     3222621.622    13857652.534     3222502.658    13857497.567
     3222332.196    13857236.373      3222274.12    13857139.108
     3222211.507    13857049.884     3221875.594    13856878.618
#Sta/Elev= 30
       0   30.37  221.89   29.27   232.4   29.66  321.98   27.14  416.59   22.26
  421.03   23.65  434.35   21.52  449.01   20.03   479.3    9.16   486.4    5.06
  487.12    4.02  487.59    2.32  494.24    2.74  501.17    4.25  501.44    3.68
  502.42     6.7  506.57    7.81  518.74    9.29  553.83    18.8  577.58   19.37
  593.19   18.83  601.23   19.11  609.49   20.49  616.42   20.27  652.88   22.58
  729.87   26.12  804.26   28.42  934.79   28.08   999.2   29.07 1106.92   29.42
#Mann= 3 , 0 , 0
       0      .1       0   479.3     .06       0  506.57      .1       0
Bank Sta=479.3,506.57
XS Rating Curve= 0
Exp/Cntr=.3,.1

Type RM Length L Ch R = 1 ,6605.805,96.52,95.79,79.79
BEGIN DESCRIPTION:
461v3 - xs 4/4 of I-10 Feeder Road Rest Stop
Bank Station offset =      4485
END DESCRIPTION:
XS GIS Cut Line= 6
     3222813.076    13857505.847     3222522.853    13857209.449
     3222475.605    13857144.143     3222453.835    13857122.987
     3222391.121    13857044.784     3221912.745    13856845.378
#Sta/Elev= 30
       0   30.67  131.42   29.29   245.9   29.44  277.67   29.83  338.29   25.04
     393   23.22  402.88    23.7  407.83   22.44  429.24   18.93  438.96   18.06
     443   19.15  463.39   19.17  495.48    8.36  507.67     4.1  508.54    3.31
  508.62    2.41  515.15    1.78  520.77    2.26  521.55    3.33  525.48    6.02
  531.56    6.76  542.22   11.07  552.57   16.26  578.12   17.55  626.03   21.65
  649.81   22.58  855.99    29.8 1024.57   29.11  1052.4   29.51  1144.3   29.59
#Mann= 3 , 0 , 0
       0      .1       0  495.48     .06       0  525.48      .1       0
Bank Sta=495.48,525.48
XS Rating Curve= 0
Exp/Cntr=.5,.3

Type RM Length L Ch R = 1 ,6510.014,401.54,380.38,367.95
BEGIN DESCRIPTION:
Copy of 461v3 - xs 3/4 of I-10 Feeder Road Rest Stop
Bank Station offset =      4465
END DESCRIPTION:
XS GIS Cut Line= 5
     3222920.108    13857429.689     3222749.268    13857314.423
     3222582.544       13857123.     3222533.145    13857067.425
     3221932.298    13856814.093
#Sta/Elev= 30
       0   30.31     180      27  206.88   27.71   278.4   27.53  326.45    24.7
  386.39   23.87  417.45   22.02  422.28   23.42  448.64   18.65  458.36   17.78
   462.4   18.87  482.79   18.89  514.88    8.08  527.07    3.82  527.94    3.03
  528.02    2.13  534.55     1.5  540.17    1.98  540.95    3.05  544.88    5.74
  550.96    6.48  561.62   10.79  571.97   15.98  597.52   17.27  638.64   20.84
  665.72   22.52  766.54   25.85  855.13    26.9  913.22   29.49 1186.36   29.59
#Mann= 3 , 0 , 0
       0      .1       0  514.88     .06       0  544.88      .1       0
#XS Ineff= 2 , 0
       0  497.84   25.17  561.62       0   25.17
Permanent Ineff=
       F       F
Bank Sta=514.88,544.88
XS Rating Curve= 0
Exp/Cntr=.5,.3

Type RM Length L Ch R = 2 ,6320    ,,,
BEGIN DESCRIPTION:
461s2, I 10
END DESCRIPTION:
Bridge Culvert--1,0,-1,-1, 0
Deck Dist Width WeirC Skew NumUp NumDn MinLoCord MaxHiCord MaxSubmerge Is_Ogee
50,279.5,2.6,0, 8, 8, , , .95, 0, 0,0,,
       0     335  427.08  479.52  526.89  572.74  692.32    1200
   26.03   26.03   26.03   25.43   25.17   25.06   25.74   25.74
                                                                
  157.41  322.41  429.49  481.93   529.3  575.15  694.73 1357.41
   26.03   26.03   26.03   25.43   25.17   25.06   25.74   25.74
                                                                
BR Coef=-1 , 0 , 0 ,, 0 ,,,.8,0,,0,
WSPro=,,,, 1 ,,,, 0 ,,,, 0 ,,,,-1 ,-1 ,-1 , 0 , 0 , 0 , 0 , 0
Multiple Barrel Culv=1,7,,318.5,.012,.5,1,1,1,2.91,2.55, 3,Culvert #1  , 0 ,31
  519.26  522.59     530  532.41  540.64   542.7
Culvert Bottom n=.012
BC Design=,, 0 ,, 0 ,,,,,,

Type RM Length L Ch R = 1 ,6129.636,40.34,38.67,35.33
BEGIN DESCRIPTION:
461s2d - xs 2/4 of I-10 Feeder Road Rest Stop
Bank Station offset =      4635
END DESCRIPTION:
XS GIS Cut Line= 6
     3223105.514    13856828.197     3222926.302    13856808.036
     3222911.741    13856806.915     3222756.566    13856759.386
     3222676.525    13856739.711     3222361.784    13856627.704
#Sta/Elev= 30
  157.41   24.37  215.98   26.18  229.06   25.98   241.2   26.45  254.55   26.19
  263.21    25.7  282.74   26.12  317.42   25.35  333.86   24.13  414.63   20.61
  457.99   17.87  494.44    9.39  514.88    4.23  519.71    2.23  522.23    -.66
  541.32    -.27  543.97    2.21  549.39    5.44  567.29    8.21  600.27   15.17
  653.76    15.4  658.15   14.25  690.61   17.17  710.28    21.7  717.64   23.77
  721.84    24.5  731.16   25.19  817.37    26.4  866.69   26.66  931.15   26.59
#Mann= 3 , 0 , 0
  157.41      .1       0  514.88     .06       0  549.39      .1       0
#XS Ineff= 2 , 0
  157.41  494.44   25.17  567.29  157.41   25.17
Permanent Ineff=
       F       F
Bank Sta=514.88,549.39
XS Rating Curve= 0
Exp/Cntr=.5,.3

Type RM Length L Ch R = 1 ,6090.962,965.83,985.92,991.07
BEGIN DESCRIPTION:
Copy of 461s2d - xs 1/4 of I-10 Feeder Road Rest Stop
Bank Station offset =      4637
END DESCRIPTION:
XS GIS Cut Line= 6
     3223128.167    13856797.255     3222948.955    13856777.094
     3222934.394    13856775.974      3222779.22    13856728.445
     3222699.178     13856708.77     3222384.438    13856596.762
#Sta/Elev= 30
       0    28.4   33.37   22.95   61.66   20.34  100.97   19.04  118.74   18.77
  135.03   19.35  175.04   22.32  211.06   21.78  253.07   19.78  255.67    20.5
  299.03   17.76  335.48    9.28  355.92    4.12  360.75    2.12  363.27    -.77
  382.36    -.38  385.01     2.1  390.43    5.33  408.33     8.1  441.31   15.06
   494.8   15.29  495.19   14.03  506.77   14.05  527.16   15.27  556.63   20.21
  574.13    24.2   600.3   24.83  644.59   25.24  661.32   26.28  773.74   27.03
#Mann= 3 , 0 , 0
       0      .1       0  355.92     .06       0  390.43      .1       0
Bank Sta=355.92,390.43
XS Rating Curve= 0
Exp/Cntr=.3,.1

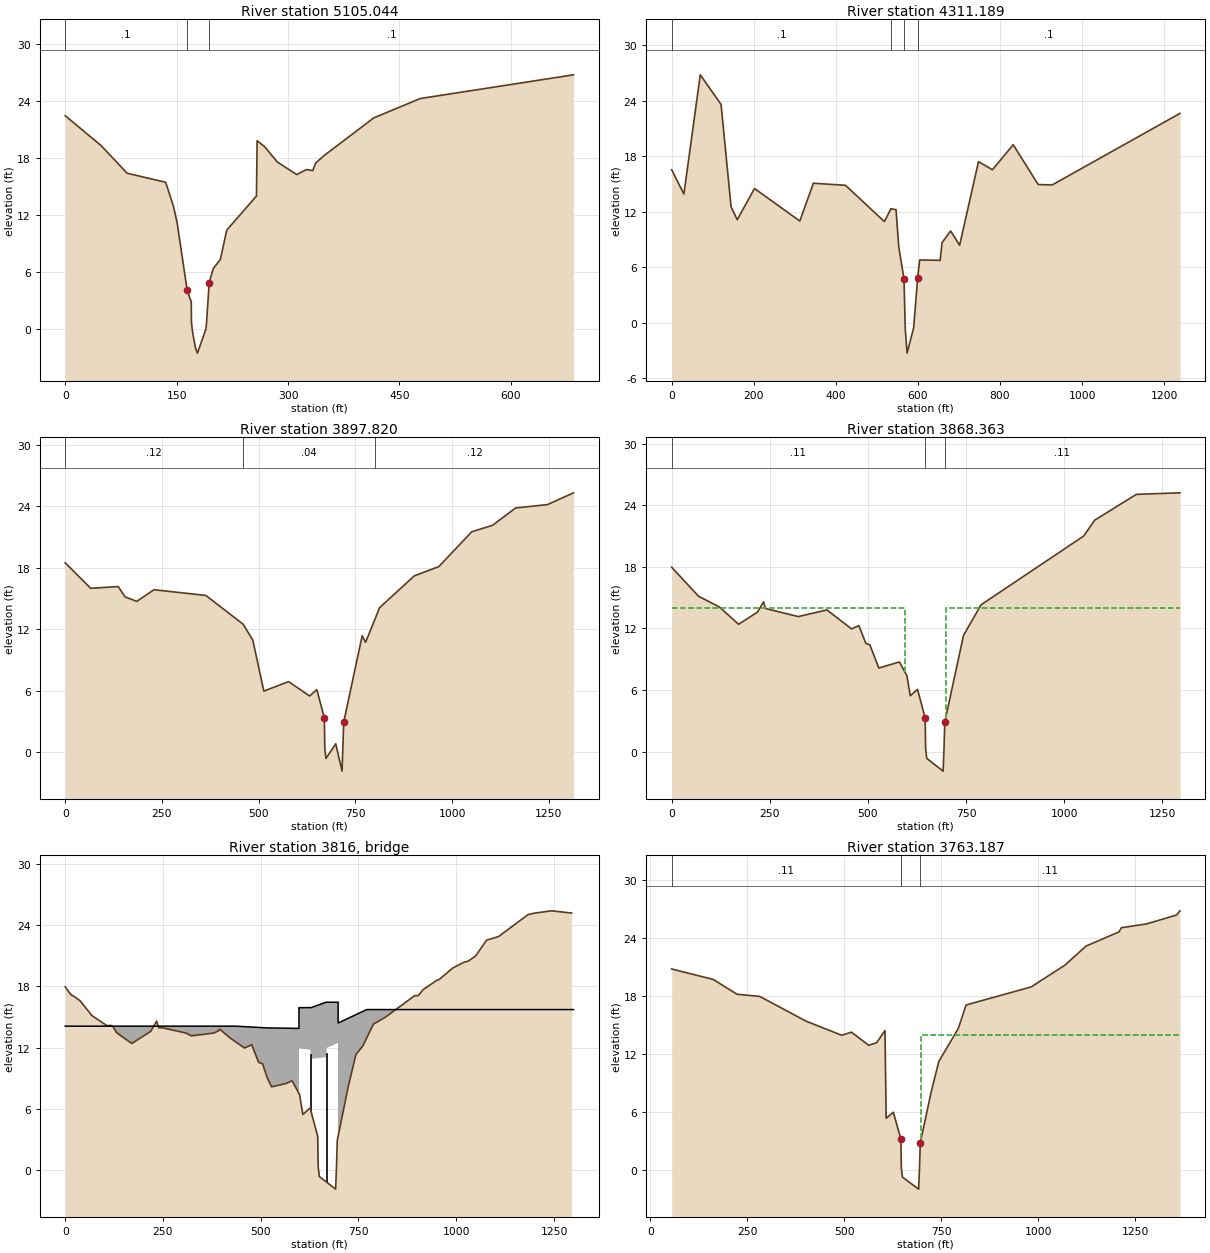
Type RM Length L Ch R = 1 ,5105.044,756.42,793.85,825.26
BEGIN DESCRIPTION:
461v2
Bank Station offset =      4822
END DESCRIPTION:
XS GIS Cut Line= 5
     3223230.962    13856229.268     3223084.711    13856171.222
     3223027.806    13856151.092       3222989.5     13856137.46
     3222588.198    13855994.647
#Sta/Elev= 30
       0   22.47   48.16   19.33   83.36    16.4  135.24   15.45  145.62   12.95
  150.66   11.18  164.24    4.04  169.69    2.84  169.98     .66  171.61    -.42
  175.45   -2.04  178.05   -2.57   189.5    -.02   190.3     .66  193.85    4.87
  199.37    6.36  208.86     7.3  217.47    10.4  257.47      14  258.37   19.83
  268.43   19.21  285.45   17.59  311.72   16.26   324.7   16.79  333.22   16.68
  337.26   17.48  348.63   18.27  415.44   22.24  477.96   24.28  684.33   26.78
#Mann= 3 , 0 , 0
       0      .1       0  164.24     .06       0  193.85      .1       0
Bank Sta=164.24,193.85
XS Rating Curve= 0
Exp/Cntr=.3,.1

Type RM Length L Ch R = 1 ,4311.189,350.9,413.37,340.62
BEGIN DESCRIPTION:
461v1
Bank Station offset =      4426
Channel RL> both OB due to fact that river curves and overbanks more direct
END DESCRIPTION:
XS GIS Cut Line= 4
     3223918.651     13855691.62     3223495.268    13855695.984
     3223392.696    13855484.293       3222847.1    13855680.708
#Sta/Elev= 30
       0   16.54    29.8   13.91   69.67   26.81  120.34   23.61  144.67   12.55
  159.68   11.13  201.84   14.51  312.23   10.99  345.19   15.08  423.41   14.86
  518.33   10.93   534.1   12.32  546.69   12.22  553.16    8.24     566    4.73
  569.17    -.72  573.57    -3.3  589.59    -.55  599.24    4.82  604.28    6.78
  654.25    6.74  658.64    8.64  679.64    9.92   701.6    8.37  747.61   17.42
  781.46   16.54  832.17   19.25  892.97   14.94  927.27    14.9 1238.51   22.64
#Mann= 4 ,-1 , 0
       0      .1       0   534.1      .1       0     566     .06       0
  599.24      .1       0
Bank Sta=566,599.24
XS Rating Curve= 0
Exp/Cntr=.3,.1

Type RM Length L Ch R = 1 ,3897.820,24.75,29.46,25.01
BEGIN DESCRIPTION:
461s1u - xs 4/4 of State Hwy 330
Bank Station offset =      4316
Channel RL> both OB due to fact that river curves and overbanks more direct
END DESCRIPTION:
XS GIS Cut Line= 6
     3223980.735    13855128.722      3223389.05    13855364.927
     3223349.519    13855365.123     3223299.758    13855371.446
     3223028.814    13855484.424     3222759.089     13855600.02
#Sta/Elev= 30
       0   18.48   65.96   15.99  136.93   16.16  154.84   15.15  184.96   14.71
  229.46   15.85  363.64   15.29  459.83   12.48  484.98   10.91  513.34    5.94
  577.33    6.87  631.85    5.46  650.35    6.09  669.72    3.32  671.02     .29
  673.89    -.64  699.21     .79  715.56   -1.88  719.77     2.9  767.52   11.35
  776.36   10.71  801.41   13.05  812.64    14.1   902.5   17.21  965.62   18.11
  1050.6   21.51 1104.65   22.15 1164.09   23.84 1246.61   24.17 1313.79   25.32
#Mann= 3 ,-1 , 0
       0     .12       0  459.83     .04       0  801.41     .12       0
Bank Sta=669.72,719.77
XS Rating Curve= 0
Exp/Cntr=.5,.3

Type RM Length L Ch R = 1 ,3868.363,111.17,105.18,101.94
BEGIN DESCRIPTION:
Copy of 461s1u - xs 3/4 of State Hwy 330
Bank Station offset =      4340
END DESCRIPTION:
XS GIS Cut Line= 6
     3223972.226    13855096.652     3223390.953    13855338.789
     3223362.806    13855338.951      3223310.28     13855345.76
     3223042.101    13855458.252     3222772.376    13855573.848
#Sta/Elev= 30
       0   17.96   68.51   15.13  121.43   14.09  170.46    12.4  218.53   13.58
  234.02   14.59  238.94   13.94  322.64   13.15   395.4    13.8   458.5   11.95
  477.03   12.27  494.72   10.54  504.87    10.4  527.74    8.14  580.33    8.73
  599.29    7.39  607.85    5.43  626.35    6.06  645.72    3.29  647.02     .26
  649.89    -.67  691.56   -1.91   693.9     .36  695.77    2.87  743.52   11.32
  788.28    14.3 1049.72      21 1077.53   22.54 1183.82   25.06 1295.07   25.21
#Mann= 3 , 0 , 0
       0     .11       0  645.72     .04       0  695.77     .11       0
#XS Ineff= 2 , 0
       0     595      14  697.91       0      14
Permanent Ineff=
       F       F
Bank Sta=645.72,695.77
XS Rating Curve= 0
Exp/Cntr=.5,.3

Type RM Length L Ch R = 3 ,3816    ,,,
BEGIN DESCRIPTION:
461s1, State Hwy 330 (West)
END DESCRIPTION:
Bridge Culvert--1,0,-1,-1, 0
Deck Dist Width WeirC Skew NumUp NumDn MinLoCord MaxHiCord MaxSubmerge Is_Ogee
34.74,35.7,2.6,0, 15, 15, , , .95, 0, 0,0,,
       0  435.78  515.81  597.79  597.81  597.99  626.99  628.99  666.87  668.87
  697.57  698.02  698.02  770.96    1300
    14.1    14.1   13.93   13.88   15.92   15.92   15.92   15.92   16.45   16.45
   16.45   16.45   14.41   15.73   15.73
                                           11.92   11.78   10.88   11.06   11.96
   12.45
      56  435.78  515.81  597.79  597.81  597.99  626.99  628.99  666.87  668.87
  697.57  698.02  698.02  770.96    1355
    14.1    14.1   13.93   13.88   15.92   15.92   15.92   15.92   16.45   16.45
   16.45   16.45   14.41   15.73   15.73
                                           11.92   11.78   10.88   11.06   11.96
   12.45
Pier Skew, UpSta & Num, DnSta & Num=  ,627.99, 4 ,627.99, 4 , 3 , 3 , 0 ,,
    1.35    1.35       2       2
      -5    8.78    8.78   11.78
    1.35    1.35       2       2
      -5    8.78    8.78   11.78
Pier Skew, UpSta & Num, DnSta & Num=  ,667.87, 4 ,667.87, 4 , 3 , 3 , 0 ,,
    1.35    1.35       2       2
      -5    8.96    8.96   11.96
    1.35    1.35       2       2
      -5    8.96    8.96   11.96
BR Coef=-1 , 0 , 0 ,, 0 ,,,.8,-1,,0,
WSPro=,,,, 1 ,,,, 0 ,,,, 0 ,,,,-1 ,-1 ,-1 , 0 , 0 , 0 , 0 , 0
BR U #Sta/Elev= 63
       0   17.96   14.33    17.2   25.57   16.95   38.46   16.58   68.51   15.13
  107.13   14.14  115.97   14.18  121.43   14.09  131.45   13.46  166.01   12.51
  167.31   12.48  170.46    12.4  218.53   13.58  234.02   14.59  238.94   13.94
  248.47   13.94  308.11   13.43  322.64   13.15  379.75   13.42  391.72   13.63
   395.4    13.8  421.03   12.96   458.5   11.95  469.19   12.14  477.03   12.27
  479.18   12.06  494.72   10.54  504.87    10.4  516.43    9.05  527.74    8.14
  564.53    8.46  580.33    8.73  599.29    7.39  607.85    5.43  626.35    6.06
  645.72    3.29  647.02     .26  649.89    -.67  691.56   -1.91   693.9     .36
  695.77    2.87  724.05     8.2  743.52   11.32  761.01   12.14  788.28    14.3
  815.89   14.91  820.06   15.01  893.84    17.1  903.04    17.1  915.34   17.69
  949.68   18.59   956.2   18.68  991.05   19.81 1001.62   20.02 1021.33   20.41
 1029.85   20.47 1049.72      21 1077.53   22.54 1108.46   22.91 1183.82   25.06
 1200.84   25.21 1244.35   25.43 1295.07   25.21
BR U #Mann= 3
       0     .11  645.72    .035  695.77     .11
BR D #Sta/Elev= 57
      55   20.82   77.21   20.75   79.75   20.67    81.8   20.65  108.66   20.12
  113.08   20.07   113.9   20.05  162.08   19.74  223.49    18.2  230.71   18.14
  275.46   17.91  281.87   17.98  313.36   17.45  356.44   16.48  372.51   16.33
  401.51   15.41  421.23   15.28   451.2   14.91   493.1   13.95  510.62   14.35
  518.41   14.27  546.16   13.42  562.63   12.92  583.21   13.17  607.85    5.34
  626.35    5.97  645.72     3.2  647.02     .17  649.89    -.76  691.56      -2
   693.9     .27  695.77    2.78  724.05    8.11  743.52   11.23  791.56   14.62
  792.43   14.67  793.81   14.65  804.27   16.19  813.87   17.09  823.66    17.1
  870.21   17.47  910.34   18.14  981.57   18.96 1028.49   20.41 1048.98   20.82
    1069   21.23 1078.57   21.63 1122.79   23.19 1155.94   23.67 1190.97   24.52
 1207.69   24.66 1214.31    25.1 1222.68   24.98 1278.58   25.49 1318.97   26.08
 1356.13   26.41 1365.23   26.85
BR D #Mann= 3
      55     .11  645.72    .035  695.77     .11
BR D Banks=645.72,695.77
BC Design=,, 0 ,, 0 ,,,,,,

Type RM Length L Ch R = 1 ,3763.187,30.59,30.39,31
BEGIN DESCRIPTION:
Copy of 461s1u - xs 2/4 of State Hwy 330
Bank Station offset =      4395
LOB and ROB > channel reach length (Stream is more direct, OB are curved.)
END DESCRIPTION:
XS GIS Cut Line= 4
     3223918.147    13855004.718     3223463.289    13855190.031
      3222997.71    13855379.938     3222703.661    13855496.333
#Sta/Elev= 30
      55   20.82  162.08   19.74  223.49    18.2  281.87   17.98  401.51   15.41
   493.1   13.95  518.41   14.27  562.63   12.92  583.21   13.17  604.81   14.44
  607.85    5.34  626.35    5.97  645.72     3.2  647.02     .17  649.89    -.76
  691.56      -2   693.9     .27  695.77    2.78  724.05    8.11  743.52   11.23
  793.81   14.65  813.87   17.09  981.57   18.96    1069   21.23 1122.79   23.19
 1207.69   24.66 1214.31    25.1 1278.58   25.49 1356.13   26.41 1365.23   26.85
#Mann= 3 , 0 , 0
      55     .11       0  645.72     .04       0  695.77     .11       0
#XS Ineff= 2 , 0
      55  597.99      14  697.91      55      14
Permanent Ineff=
       F       F
Bank Sta=645.72,695.77
XS Rating Curve= 0
Exp/Cntr=.5,.3

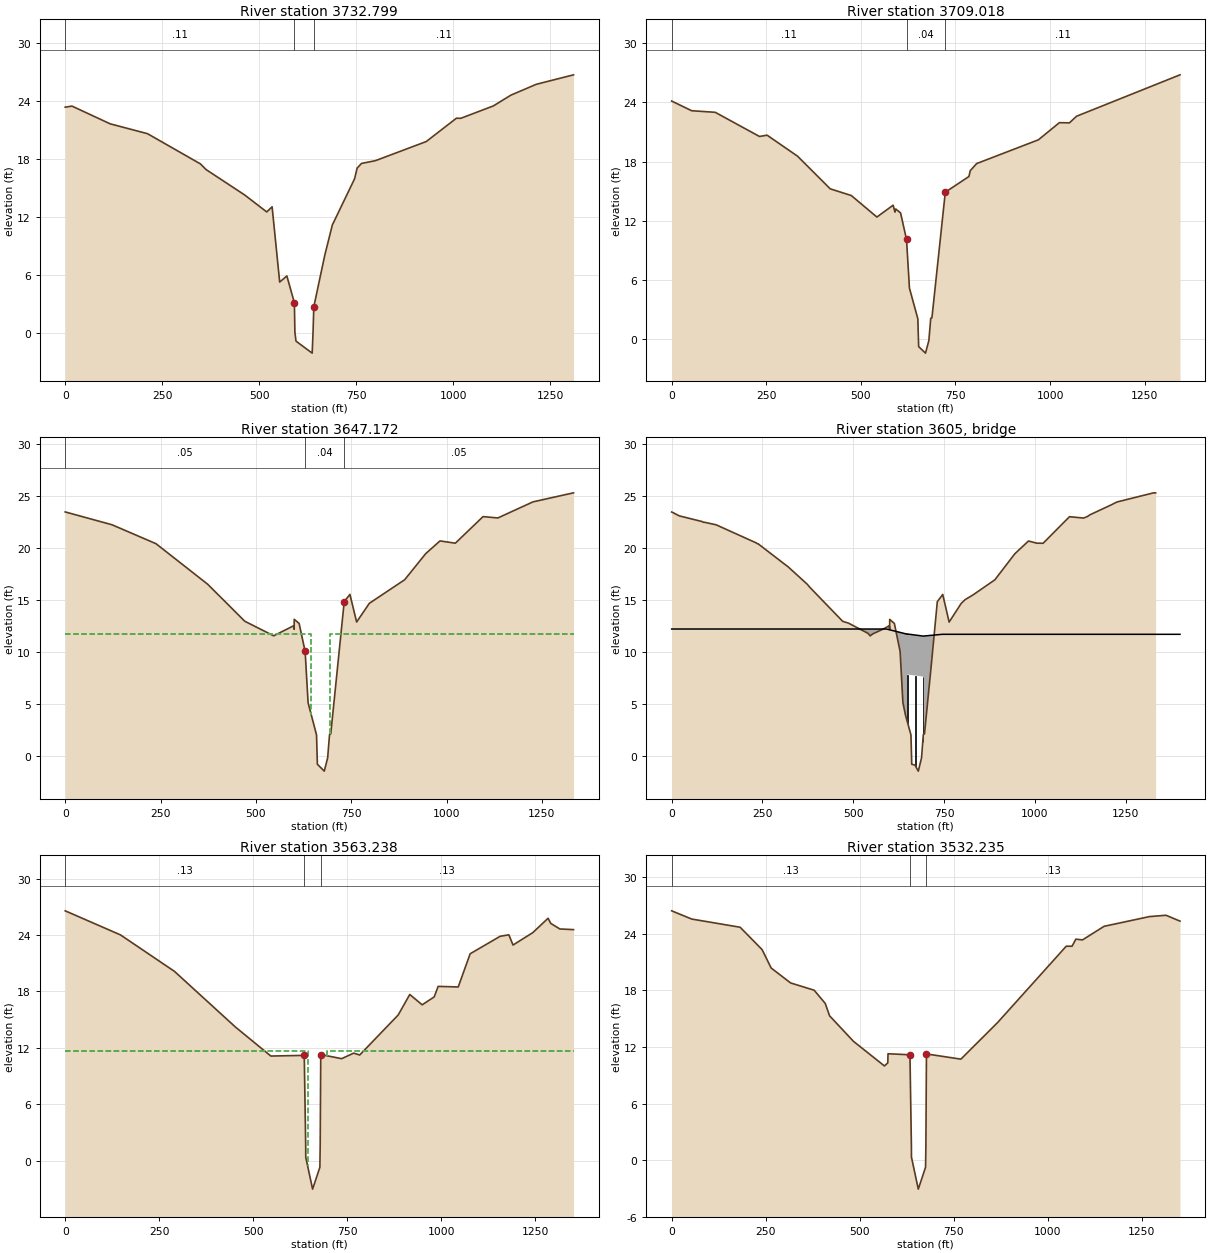
Type RM Length L Ch R = 1 ,3732.799,45.26,23.78,9.92
BEGIN DESCRIPTION:
Copy of 461s1u - xs 1/4 of State Hwy 330
Bank Station offset =      4395
END DESCRIPTION:
XS GIS Cut Line= 4
     3223908.293    13854975.966     3223453.435    13855161.279
     3222987.856    13855351.186     3222693.806     13855467.58
#Sta/Elev= 30
       0   23.37   17.55   23.48  115.86   21.65  212.28   20.63   348.6   17.51
  362.98   16.93  462.33   14.31  519.45   12.55  533.31   13.08  552.85    5.31
  571.35    5.94  590.72    3.17  592.02     .14  594.89    -.79  636.56   -2.03
   638.9     .24  640.77    2.75  669.05    8.08  688.52    11.2  745.94   15.98
  752.38   17.07  763.76   17.56   799.2   17.84  930.63   19.82 1008.39   22.23
 1019.65   22.22 1103.62    23.5 1148.71   24.61 1214.09   25.73 1310.23   26.71
#Mann= 3 , 0 , 0
       0     .11       0  590.72     .04       0  640.77     .11       0
Bank Sta=590.72,640.77
XS Rating Curve= 0
Exp/Cntr=.3,.1

Type RM Length L Ch R = 1 ,3709.018,47.09,61.85,74.05
BEGIN DESCRIPTION:
461v13 - xs 4/4 of  "HCFCD ditch"
Bank Station offset =      4338
END DESCRIPTION:
XS GIS Cut Line= 6
      3223919.12    13854934.155     3223348.929    13855155.312
     3223341.977    13855157.952     3223309.448    13855209.702
     3223064.003     13855305.81     3222691.782     13855451.08
#Sta/Elev= 30
       0   24.13   52.83   23.15  115.07   22.99  232.02   20.54   252.2   20.67
  332.65   18.54  418.95   15.23   474.7   14.55  542.32   12.37  585.21   13.57
  590.07   12.87  591.96   13.19  604.87   12.79   620.6    10.1  628.35    5.16
  650.48    2.06   652.7    -.77  670.78   -1.43  679.65    -.15  684.61     2.1
   687.8    2.16  723.07   14.89  785.57   16.48  789.03   17.07   805.9   17.79
  969.07    20.2 1024.64   21.94  1051.1   21.92 1069.96   22.59 1343.29   26.79
#Mann= 3 , 0 , 0
       0     .11       0   620.6     .04       0  723.07     .11       0
Bank Sta=620.6,723.07
XS Rating Curve= 0
Exp/Cntr=.5,.3

Type RM Length L Ch R = 1 ,3647.172,80.04,83.93,85.19
BEGIN DESCRIPTION:
Copy of 461v13 - xs 3/4 of  "HCFCD ditch"
Bank Station offset =      4330
END DESCRIPTION:
XS GIS Cut Line= 6
     3223902.619     13854862.55      3223366.91     13855093.74
     3223343.215    13855107.458     3223292.947    13855138.097
     3223047.503    13855234.205     3222675.282    13855379.476
#Sta/Elev= 30
       0   23.47  122.37   22.24  238.13   20.41  373.52   16.51  471.01   12.94
  546.64   11.54  599.12   12.51  600.35   12.17  600.47   13.13  613.38   12.73
  629.11   10.04  636.86     5.1  658.99       2  661.21    -.83  679.29   -1.49
  688.16    -.21  693.12    2.04  696.31     2.1  731.58   14.83  746.54   15.53
  764.17   12.87  797.47   14.67  890.11   16.94  945.15   19.45  982.73   20.68
 1022.96   20.46 1095.63   23.02  1134.4   22.89 1226.66   24.44 1332.87   25.31
#Mann= 3 , 0 , 0
       0     .05       0  629.11     .04       0  731.58     .05       0
#XS Ineff= 2 , 0
       0     645   11.69     695       0   11.69
Permanent Ineff=
       F       F
Bank Sta=629.11,731.58
XS Rating Curve= 0
Exp/Cntr=.5,.3

Type RM Length L Ch R = 3 ,3605    ,,,
BEGIN DESCRIPTION:
461s8, State Hwy. 330 (East)
END DESCRIPTION:
Bridge Culvert--1,0,-1,-1, 0
Deck Dist Width WeirC Skew NumUp NumDn MinLoCord MaxHiCord MaxSubmerge Is_Ogee
16.8,50.4,2.6,0, 9, 9, , , .95, 0, 0,0,,
       0  591.43  648.95  648.96  649.03   692.6   692.7   745.3    1400
    12.2    12.2    11.7    11.7   11.72   11.52   11.52   11.69   11.69
                             7.8    7.82    7.62
       0  591.43  648.95  648.96  649.03   692.6   692.7   745.3    1400
    12.2    12.2    11.7    11.7   11.72   11.52   11.52   11.69   11.69
                             7.8    7.82    7.62
Pier Skew, UpSta & Num, DnSta & Num=  ,649.69, 2 ,649.69, 2 , 0 , 0 , 0 ,,
    1.35    1.35
       0      10
    1.35    1.35
       0      10
Pier Skew, UpSta & Num, DnSta & Num=  ,670.76, 2 ,670.76, 2 , 0 , 0 , 0 ,,
       2       2
       0      10
       2       2
       0      10
Pier Skew, UpSta & Num, DnSta & Num=  ,691.63, 2 ,691.63, 2 , 0 , 0 , 0 ,,
    1.35    1.35
       0      10
    1.35    1.35
       0      10
BR Coef=-1 , 0 , 0 ,, 0 ,,,.8,-1,,0,
WSPro=,,,, 1 ,,,, 0 ,,,, 0 ,,,,-1 ,-1 ,-1 , 0 , 0 , 0 , 0 , 0
BR U #Sta/Elev= 60
       0   23.47    3.21   23.42    5.36   23.39    8.11   23.33   21.02    23.1
   84.09   22.55   86.79   22.49   91.09   22.48  122.37   22.24  231.43   20.52
  236.82   20.41  238.13   20.41  313.56   18.38  319.81   18.22  373.52   16.51
  380.75   16.21  471.01   12.94  486.79   12.77   540.9   11.78  546.64   11.54
  553.88   11.73  583.47   12.21  585.56   12.25  599.12   12.51  599.45   12.43
  600.35   12.17  600.47   13.13  613.38   12.73  629.11   10.04  636.86     5.1
  644.05    3.89  658.99       2  661.21    -.83  670.12    -.91  679.29   -1.49
  688.16    -.21  693.12    2.04  696.31     2.1  716.37    9.21  731.58   14.83
  746.54   15.53  764.17   12.87  797.47   14.67  808.61   15.04  830.17   15.49
  890.11   16.94   933.3   18.91  945.15   19.45  982.73   20.68 1005.35   20.47
 1022.96   20.46 1095.63   23.02  1134.4   22.89 1145.09   23.04 1151.77    23.2
 1211.24   24.17 1226.66   24.44 1326.28   25.31 1330.91   25.32 1332.87   25.31
BR U #Mann= 3
       0     .05  629.11     .04  731.58     .05
BR D #Sta/Elev= 60
       0   23.47    3.21   23.42    5.36   23.39    8.11   23.33   21.02    23.1
   84.09   22.55   86.79   22.49   91.09   22.48  122.37   22.24  231.43   20.52
  236.82   20.41  238.13   20.41  313.56   18.38  319.81   18.22  373.52   16.51
  380.75   16.21  471.01   12.94  486.79   12.77   540.9   11.78  546.64   11.54
  553.88   11.73  583.47   12.21  585.56   12.25  599.12   12.51  599.45   12.43
  600.35   12.17  600.47   13.13  613.38   12.73  629.11   10.04  636.86     5.1
  644.05    3.89  658.99       2  661.21    -.83  670.12    -.91  679.29   -1.49
  688.16    -.21  693.12    2.04  696.31     2.1  716.37    9.21  731.58   14.83
  746.54   15.53  764.17   12.87  797.47   14.67  808.61   15.04  830.17   15.49
  890.11   16.94   933.3   18.91  945.15   19.45  982.73   20.68 1005.35   20.47
 1022.96   20.46 1095.63   23.02  1134.4   22.89 1145.09   23.04 1151.77    23.2
 1211.24   24.17 1226.66   24.44 1326.28   25.31 1330.91   25.32 1332.87   25.31
BR D #Mann= 3
       0     .05  629.11     .04  731.58     .05
BR D Banks=629.11,731.58
BC Design=,, 0 ,, 0 ,,,,,,

Type RM Length L Ch R = 1 ,3563.238,31.67,31,31.16
BEGIN DESCRIPTION:
461s8d - xs 2/4 of  "HCFCD ditch"
Bank Station offset =      4342
LOB and ROB > channel reach length (Stream is more direct, OB are curved.)
END DESCRIPTION:
XS GIS Cut Line= 6
     3223870.784    13854796.084     3223345.048    13855020.982
     3223305.887     13855040.38     3223265.901     13855058.42
     3223165.319    13855097.743     3222615.288    13855295.993
#Sta/Elev= 30
       0   26.58  146.96   24.02  290.58   20.14  452.39   14.23  546.89   11.13
  635.83    11.2  639.74    1.37  639.79     .37     658   -3.03  677.34    -.71
   678.2    1.55   679.7   11.29  735.21   10.85  767.38   11.44  783.29   11.24
  885.73    15.5  916.46   17.68  949.51   16.58   981.4   17.42  991.95   18.54
 1045.38   18.48 1077.07   22.01 1156.79   23.87 1179.99   24.03 1191.13   22.94
 1243.69   24.26 1284.35   25.79 1291.51   25.24 1315.71   24.65 1352.05   24.58
#Mann= 3 , 0 , 0
       0     .13       0  635.83     .05       0   679.7     .13       0
#XS Ineff= 2 , 0
       0     645   11.69     695       0   11.69
Permanent Ineff=
       F       F
Bank Sta=635.83,679.7
XS Rating Curve= 0
Exp/Cntr=.5,.3

Type RM Length L Ch R = 1 ,3532.235,1038.07,1103.78,1037.49
BEGIN DESCRIPTION:
Copy of 461s8d - xs 1/4 of  "HCFCD ditch"
Bank Station offset =      4344
Channel RL> both OB due to fact that river curves and overbanks more direct
END DESCRIPTION:
XS GIS Cut Line= 6
     3223864.549    13854764.907     3223338.812    13854989.805
     3223299.135    13855010.545     3223260.121    13855027.551
     3223159.084    13855066.566     3222609.052    13855264.816
#Sta/Elev= 30
       0   26.42   53.17   25.55  182.17   24.68  240.56   22.31  264.67   20.36
  316.44   18.78  379.01   18.01  408.49   16.61  420.05    15.3  483.45    12.6
  565.89    9.99   574.9   10.31  575.48   11.28  633.83   11.17  637.74    1.34
  637.79     .34     656   -3.06  675.34    -.74   676.2    1.52   677.7   11.26
  769.34   10.71  867.28    14.6 1049.49   22.67 1064.94   22.67 1075.13   23.42
 1092.77   23.34 1150.24   24.78 1271.01   25.81 1314.92   25.95 1352.13   25.33
#Mann= 3 , 0 , 0
       0     .13       0  633.83     .05       0   677.7     .13       0
Bank Sta=633.83,677.7
XS Rating Curve= 0
Exp/Cntr=.3,.1

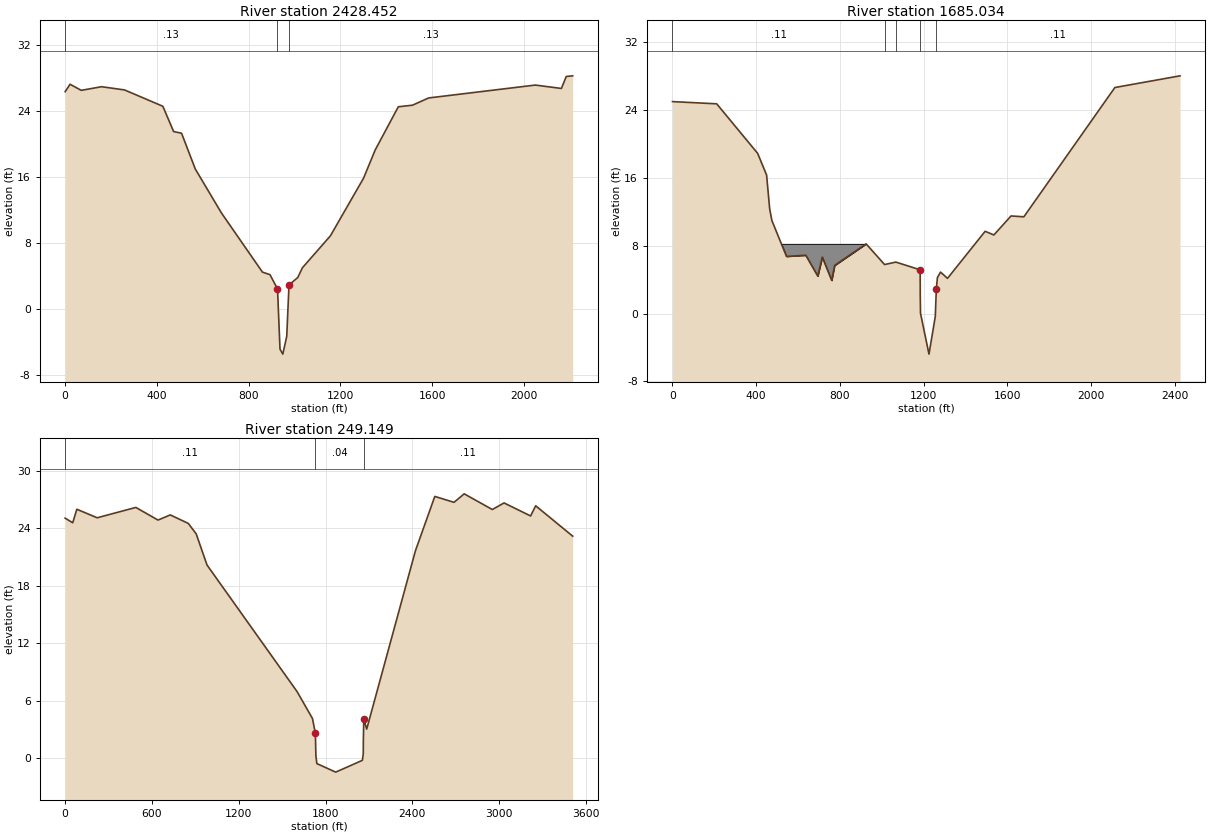
Type RM Length L Ch R = 1 ,2428.452,910.48,743.42,637.73
BEGIN DESCRIPTION:
461v14
Bank Station offset =      4051
END DESCRIPTION:
XS GIS Cut Line= 6
     3223808.943    13853804.415     3222995.402    13854122.741
     3222812.365     13854151.68     3222279.892    13854470.006
     3221927.924    13854687.047     3221826.638    13854752.159
#Sta/Elev= 30
       0    26.3   21.43    27.2   69.95   26.46  158.71    26.9  258.93   26.51
  425.96   24.53  472.93   21.47  507.66   21.26  567.38   16.93  681.67   11.59
  860.31    4.43  893.17    4.12  925.13    2.44  926.29    2.23  936.81    -4.9
  949.05   -5.51  966.21   -3.35  976.03    2.87 1014.44    3.78 1034.38    4.95
 1156.72    8.83 1301.08   15.81 1352.26   19.25 1452.73   24.47  1514.5   24.66
 1585.37   25.54 2050.23    27.1  2163.9   26.69 2185.06   28.14 2213.23   28.22
#Mann= 3 , 0 , 0
       0     .13       0  925.13     .05       0  976.03     .13       0
Bank Sta=925.13,976.03
XS Rating Curve= 0
Exp/Cntr=.3,.1

Type RM Length L Ch R = 1 ,1685.034,1436.76,1435.88,1441.49
BEGIN DESCRIPTION:
461v15
Bank Station offset =      3774
LOB and ROB reach length > channel reach length - very close to channel length.
END DESCRIPTION:
XS GIS Cut Line= 6
     3223505.086     13853117.12 3222472.768908113853625.4517425
 3222456.671859313853644.6148958 3222427.543866213853693.6725685
 3222413.746395713853712.0691957      3221566.19    13854441.067
#Sta/Elev= 30
       0   24.99  211.29   24.73  407.12   18.89  449.92   16.33  464.54   12.35
  475.17   10.97  544.94    6.74  636.85    6.88  694.47    4.42  715.87    6.66
  761.03    3.91     775    5.68  925.52    8.22 1013.89    5.78 1067.72    6.07
    1184    5.16 1184.43    2.03 1185.65     .03  1226.1   -4.78 1256.22    -.35
 1261.25    2.89 1266.36    4.24 1281.38    4.89 1314.61    4.15 1494.52     9.7
 1536.26    9.27 1618.35   11.51 1679.69   11.41 2114.72   26.65 2426.23   28.03
#Mann= 5 ,-1 , 0
       0     .11       0 1013.89     .99       0 1067.72     .11       0
    1184     .04       0 1261.25     .11       0
#Block Obstruct= 2 , 0
       0  925.52    8.22               0
Bank Sta=1184,1261.25
XS Rating Curve= 0
Exp/Cntr=.3,.1

Type RM Length L Ch R = 1 ,249.149 ,189.59,249.15,476.08
BEGIN DESCRIPTION:
461v16
Bank Station offset =      3130
END DESCRIPTION:
XS GIS Cut Line= 6
      3223295.28    13851583.366     3221758.658     13852382.65
      3221543.21     13852638.64     3221493.843    13852668.569
     3220350.762    13853080.946     3220194.764     13853144.25
#Sta/Elev= 30
       0   25.05   52.18   24.57   80.68   25.98  221.26   25.09  488.46   26.17
  641.78   24.85  726.54   25.39  851.08    24.5  905.74   23.41   980.4   20.16
 1603.17    6.94 1709.16    4.14 1729.41    2.59 1732.92     .24 1739.64    -.57
 1869.97   -1.46 2054.11    -.23 2060.52     .46 2060.68    1.55 2063.65    4.11
 2084.12    3.03 2420.99   21.65 2554.85   27.32 2687.69    26.7 2757.84   27.59
 2952.58   25.95 3033.17   26.64 3216.95   25.28  3252.1   26.34 3507.93   23.17
#Mann= 3 , 0 , 0
       0     .11       0 1729.41     .04       0 2063.65     .11       0
Bank Sta=1729.41,2063.65
XS Rating Curve= 0
Exp/Cntr=.3,.1

Chan Stop Cuts=-1